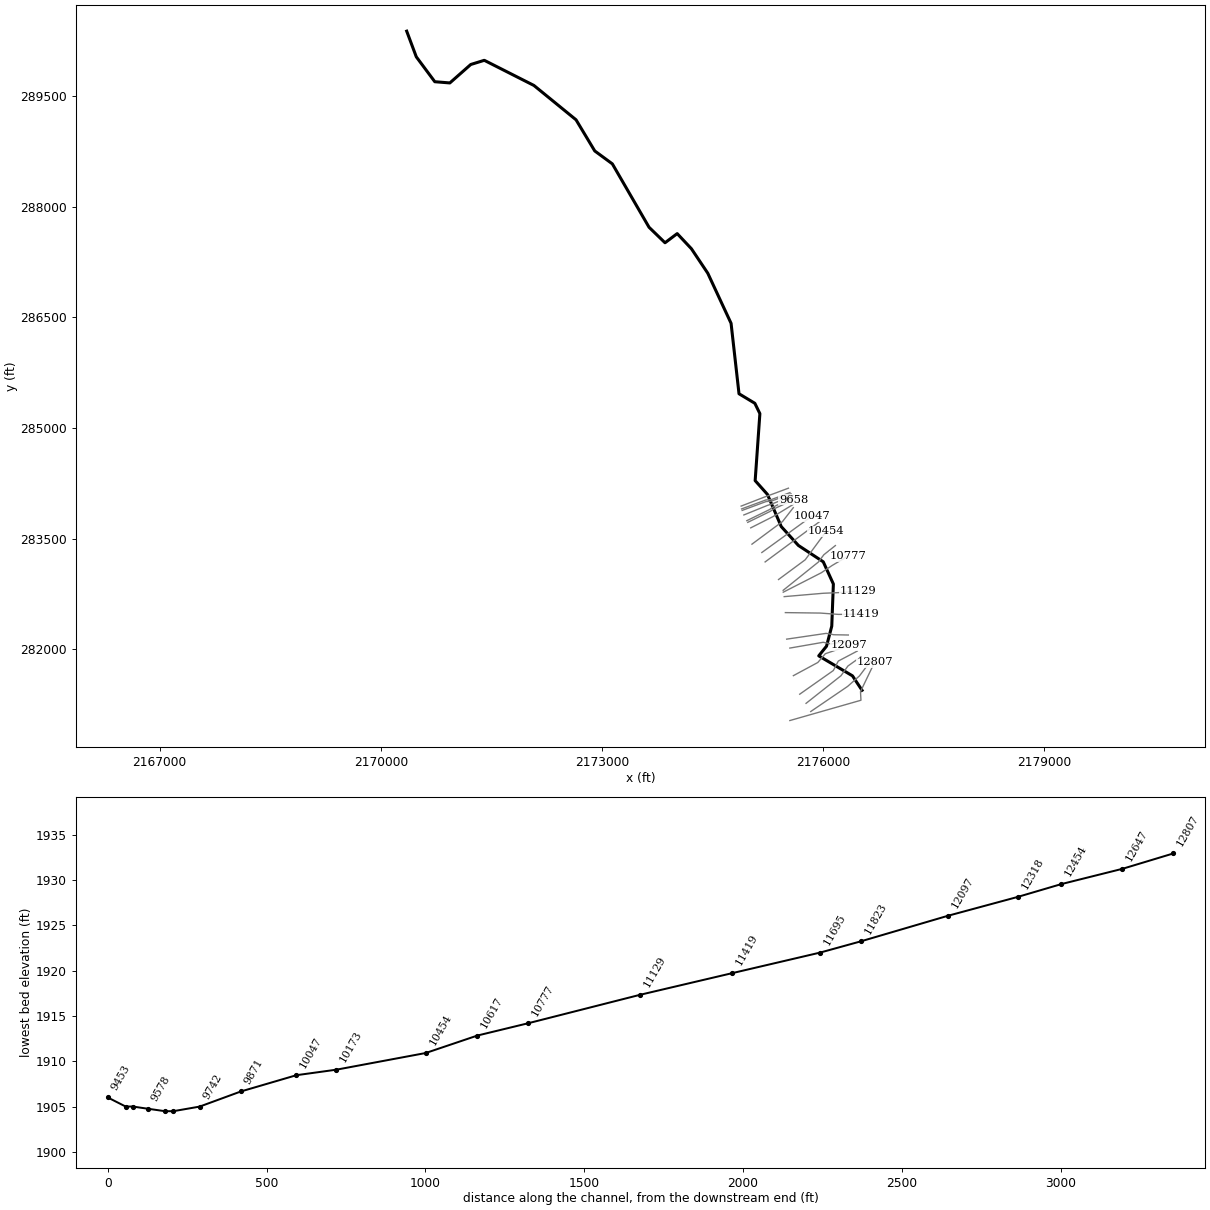
--- DRYCK1.prj (project) ---

Proj Title=DRYCK1
Current Plan=p02
Default Exp/Contr=0,0
English Units
Geom File=g01
Flow File=f01
Flow File=f02
Plan File=p01
Plan File=p02
BEGIN DESCRIPTION:
Stream Name- Dry Creek 1
Greenbrier County, WV
WV Disaster Studies / PMR
WVDHSEM-2017-2, Flood Risk Project
HEC-RAS Version: 5.0.7
Upstream Extents: Approximately 100 feet downstream of Tuckahoe Road
Downstream Extents: Approximately Confluence with Howard Creek
General Notes:
For the Hydrology the HEC-HMS version 4.2.1 was used. Rain fall grid was downloaded from the NOAA website and specified hyetogroph was used to calulate the 2016 flows in HEC-HMS. For the Multiprofile run the rainfall depth was taken from the NOAA website and hyetogrpahs were inputted into the HEC-HMS model.
END DESCRIPTION:
DSS Export Rating Curves= 0
DSS Export Rating Curve Sorted= 0
DSS Export Volume Flow Curves= 0
DXF Filename=..\..\DryCk_AE.
DXF OffsetX= 0
DXF OffsetY= 0
DXF ScaleX= 0
DXF ScaleY= 0

--- DRYCK1.p02 (plan) ---

Plan Title=Floodway
Program Version=5.07
Short Identifier=Floodway
Geom File=g01
Flow File=f02
Subcritical Flow
K Sum by GR= 0
Std Step Tol= 0.01
Critical Tol= 0.01
Num of Std Step Trials= 20
Max Error Tol= 0.3
Flow Tol Ratio= 0.001
Split Flow NTrial= 30
Split Flow Tol= 0.02
Split Flow Ratio= 0.02
Log Output Level= 0
Friction Slope Method= 1
Unsteady Friction Slope Method= 2
Unsteady Bridges Friction Slope Method= 1
Parabolic Critical Depth
Global Vel Dist= 0 , 0 , 0
Global Log Level= 0
CheckData=True
Encroach Param=-1 ,0,0, 2
Encroach River=DRYCK1
Encroach Reach=Main
Encroach Node=12807
       1    1120    1195
Encroach Node=12647
       1   717.4  774.01
Encroach Node=12454
       1     663  721.83
Encroach Node=12318
       1     590  659.82
Encroach Node=12097
       1  406.87  526.36
Encroach Node=11823
       1     400     535
Encroach Node=11695
       1  567.14   613.5
Encroach Node=11419
       1   628.4  681.52
Encroach Node=11129
       1   674.4     730
Encroach Node=10777
       1  659.31  723.06
Encroach Node=10617
       1     638     710
Encroach Node=10454
       1  540.76  608.78
Encroach Node=10173
       1   460.7     510
Encroach Node=10047
       1   410.9     460
Encroach Node=9871
       1     350     500
Encroach Node=9742
       1     240  451.35
Encroach Node=9658
       1     250     465
Encroach Node=9632
       1     260     465
Encroach Node=9578
       1     260  463.93
Encroach Node=9531
       1     275  467.35
Encroach Node=9509
       1     275   470.9
Encroach Node=9453
       1     270  447.85
Encroach Node=9273
       1  304.79  379.37
Encroach Node=8981
       1  127.62  269.14
Encroach Node=8730
       1   196.9     300
Encroach Node=8427
       1  249.18   323.8
Encroach Node=8192
       1     220  336.22
Encroach Node=8083
       1     175   303.7
Encroach Node=7823
       1     104     275
Encroach Node=7457
       1     120     191
Encroach Node=7178
       1     176     237
Encroach Node=6922
       1     210     280
Encroach Node=6593
       1     165     300
Encroach Node=6302
       1     210     350
Encroach Node=6004
       1     300  411.13
Encroach Node=5703
       1     300  493.71
Encroach Node=5607
       1     250  514.05
Encroach Node=5567
       1     230  507.22
Encroach Node=5497
       1     200  483.37
Encroach Node=5120
       1   234.9   283.3
Encroach Node=4913
       1   393.7  452.41
Encroach Node=4636
       1  364.03     483
Encroach Node=4335
       1     430     620
Encroach Node=4033
       1     440     700
Encroach Node=3701
       1   373.5     512
Encroach Node=3523
       1     347     480
Encroach Node=3334
       1     389     480
Encroach Node=3189
       1  474.62  578.54
Encroach Node=3065
       1  546.85  635.95
Encroach Node=2960
       1   610.8  671.34
Encroach Node=2908
       1  350.15  407.25
Encroach Node=2802
       1   312.6  366.36
Encroach Node=2612
       1  320.27   365.3
Encroach Node=2477
       1  333.58  383.13
Encroach Node=2237
       1   420.1   471.5
Encroach Node=1951
       1     405  496.58
Encroach Node=1778
       1     255     470
Encroach Node=1673
       1     320     485
Encroach Node=1406
       1     410     475
Encroach Node=1117
       1     310     475
Encroach Node=903
       1     441     610
Encroach Node=714
       1   567.6     650
Encroach Node=594
       1     700     790
Encroach Node=512
       1     814     927
Encroach Node=465
       1  927.14    1006
Encroach Node=407
       1   972.5  1086.5
Encroach Node=311
       1  1211.5    1274
Encroach Node=181
       1  1507.6  1581.3
Computation Interval=0.1SEC
Output Interval=1MIN
Instantaneous Interval=Max Profile
Mapping Interval=1HOUR
Computation Time Step Use Courant=        0
Computation Time Step Use Time Series=    0
Computation Time Step Count To Double=0
Computation Time Step Max Doubling=0
Computation Time Step Max Halving=0
Computation Time Step Residence Courant=0
Run HTab= 0
Run UNet= 0
Run Sediment= 0
Run PostProcess= 0
Run WQNet= 0
Run RASMapper= 0
UNET Theta= 0
UNET Theta Warmup= 0
UNET ZTol= 0
UNET ZSATol= 0
UNET MxIter= 0
UNET Max Iter WO Improvement= 0
UNET MaxInSteps= 0
UNET DtIC= 0
UNET DtMin= 0
UNET MaxCRTS= 0
UNET WFStab= 0
UNET SFStab= 0
UNET WFX= 1
UNET SFX= 1
UNET 1D Methodology=Finite Difference
UNET DSS MLevel= 1
UNET Pardiso=0
UNET DZMax Abort= 0
UNET Use Existing IB Tables= 0
UNET Froude Reduction=False
UNET Froude Limit= 0
UNET Froude Power= 0
UNET D1 Cores= 0
UNET D2 Coriolis=0
UNET D2 Cores= 0
UNET D2 Theta= 1
UNET D2 Theta Warmup= 1
UNET D2 Z Tol= 0.01
UNET D2 Volume Tol= 0.01
UNET D2 Max Iterations= 20
UNET D2 Equation= 0
UNET D2 RampUpFraction=0.1
UNET D2 TimeSlices= 1
UNET D2 BCVolumeCheck=0
UNET D1D2 MaxIter= 0
UNET D1D2 ZTol=0.01
UNET D1D2 QTol=0.1
UNET D1D2 MinQTol=1
DSS File=dss
Write IC File= 0
Write IC File at Fixed DateTime=0
Write IC File at Sim End=0
Echo Input=False
Echo Parameters=False
Echo Output=False
Write Detailed= 0
HDF Write Warmup=0
HDF Write Time Slices=0
HDF Flush=0
HDF Face Node Velocities=0
HDF Compression= 1
HDF Chunk Size= 1
HDF Spatial Parts= 1
HDF Use Max Rows=0
HDF Fixed Rows= 1
Calibration Method= 0
Calibration Iterations= 20
Calibration Max Change=0.05
Calibration Tolerance=0.2
Calibration Maximum=1.5
Calibration Minimum=0.5
Calibration Optimization Method= 1
WQ AD Non Conservative
WQ ULTIMATE=-1
WQ Max Comp Step=1HOUR
WQ Output Interval=15MIN
WQ Output Selected Increments= 0
WQ Output face flow=0
WQ Output face velocity=0
WQ Output face area=0
WQ Output face dispersion=0
WQ Output cell volume=0
WQ Output cell surface area=0
WQ Output cell continuity=0
WQ Output cumulative cell continuity=0
WQ Output face conc=0
WQ Output face dconc_dx=0
WQ Output face courant=0
WQ Output face peclet=0
WQ Output face adv mass=0
WQ Output face disp mass=0
WQ Output cell mass=0
WQ Output cell source sink temp=0
WQ Output nsm pathways=0
WQ Output nsm derived pathways=0
WQ Output MaxMinRange=-1
WQ Daily Max Min Mean=-1
WQ Daily Range=0
WQ Daily Time=0
WQ Create Restart=0
WQ Fixed Restart=0
WQ System Summary=0
WQ Write To DSS=0
WQ Use Fixed Temperature=0
Sorting and Armoring Iterations= 10
XS Update Threshold= 0.02
Bed Roughness Predictor= 0
Hydraulics Update Threshold= 0.02
Energy Slope Method= 1
Volume Change Method= 1
Sediment Retention Method= 0
XS Weighting Method= 0
Number of US Weighted Cross Sections= 1
Number of DS Weighted Cross Sections= 1
Upstream XS Weight=0
Main XS Weight=1
Downstream XS Weight=0
Number of DS XS's Weighted with US Boundary= 1
Upstream Boundary Weight= 1
Weight of XSs Associated with US Boundary= 0
Number of US XS's Weighted with DS Boundary= 1
Downstream Boundary Weight= 0.5
Weight of XSs Associated with DS Boundary= 0.5
Percentile Method= 0
Sediment Output Level= 3
Mass or Volume Output= 0
Output Increment Type= 1
Profile and TS Output Increment= 1
XS Output Flag= 0
XS Output Increment= 10
Write Gradation File= 0
Read Gradation Hotstart= 0
Write HDF5 File= 1
Write Binary Output= 1
Write DSS Sediment File= 0
SV Curve= 0
Specific Gage Flag= 0

--- DRYCK1.p01 (plan) ---

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Plan Title=Floodplain
Short Identifier=Floodplain
Geom File=g01
Flow File=f01
CheckData=False
Encroach Param=-1 ,0,0, 0

--- DRYCK1.f02 (steady flow) ---

Flow Title=Floodway
Program Version=5.07
Number of Profiles= 2
Profile Names=P100yr,Floodway
River Rch & RM=DRYCK1,Main            ,12807
    3468    3468
River Rch & RM=DRYCK1,Main            ,8981
  4232.7  4232.7
River Rch & RM=DRYCK1,Main            ,3701
  4959.7  4959.7
Boundary for River Rch & Prof#=DRYCK1,Main            , 1
Up Type= 0
Dn Type= 3
Dn Slope=0.00733
Boundary for River Rch & Prof#=DRYCK1,Main            , 2
Up Type= 0
Dn Type= 3
Dn Slope=0.00733
DSS Import GetInterval= 0
DSS Import GetPeak= 0
DSS Import FillOption= 0

--- DRYCK1.f01 (steady flow) ---

Flow Title=HMS Flow from Howard Creek Study
Program Version=5.07
Number of Profiles= 6
Profile Names=f1p,f10p,f4p,f2p,f02p,f1pplus
River Rch & RM=DRYCK1,Main            ,12807
    3468  1770.6  2376.8    2903  4965.8  4075.9
River Rch & RM=DRYCK1,Main            ,8981
  4232.7  2168.4  2911.5  3552.6  6045.9  4973.2
River Rch & RM=DRYCK1,Main            ,3701
  4959.7  2552.6  3420.7    4167  7041.6    5816
Boundary for River Rch & Prof#=DRYCK1,Main            , 1
Up Type= 0
Dn Type= 3
Dn Slope=0.00733
Boundary for River Rch & Prof#=DRYCK1,Main            , 2
Up Type= 0
Dn Type= 3
Dn Slope=0.00733
Boundary for River Rch & Prof#=DRYCK1,Main            , 3
Up Type= 0
Dn Type= 3
Dn Slope=0.00733
Boundary for River Rch & Prof#=DRYCK1,Main            , 4
Up Type= 0
Dn Type= 3
Dn Slope=0.00733
Boundary for River Rch & Prof#=DRYCK1,Main            , 5
Up Type= 0
Dn Type= 3
Dn Slope=0.00733
Boundary for River Rch & Prof#=DRYCK1,Main            , 6
Up Type= 0
Dn Type= 3
Dn Slope=0.00733
DSS Import GetInterval= 0
DSS Import GetPeak= 0
DSS Import FillOption= 0

--- DRYCK1.g01 (geometry) ---

Geom Title=1m DEM Lidar Data
Program Version=5.07

River Reach=DRYCK1          ,Main
Reach XY= 30
2176528.50003196281440.7098499492176398.63409699281636.941045675
2175941.16289907281908.0720650862176046.65711065282039.201067931
 2176117.7580183282311.3750642622176139.48894598282883.022871086
2176002.29105763 283183.865117192175665.10308371 283405.69899111
2175432.42310287283662.0409980862175244.89887165284098.563090921
2175078.47499187284285.1480195942175142.55983749285194.175072923
2175074.15807139285334.2830604332174859.39701797285463.657145524
2174751.69414939286419.3658640112174435.69904648287098.940948433
2174213.82284981287430.7841167632174020.82914131287636.322091522
2173855.81798838287512.0408440152173638.76002356287722.421000688
2173141.19507381288582.3070761872172902.43111564288757.622998499
 2172648.6389723289180.0519436782172077.06104721289646.188150522
2171403.92984755289987.2570221672171220.38297056289930.492043839
2170936.69488965289680.3468748442170732.50402507 289696.73693393
 2170481.4231624290034.4091588652170351.18687433 290382.71489269

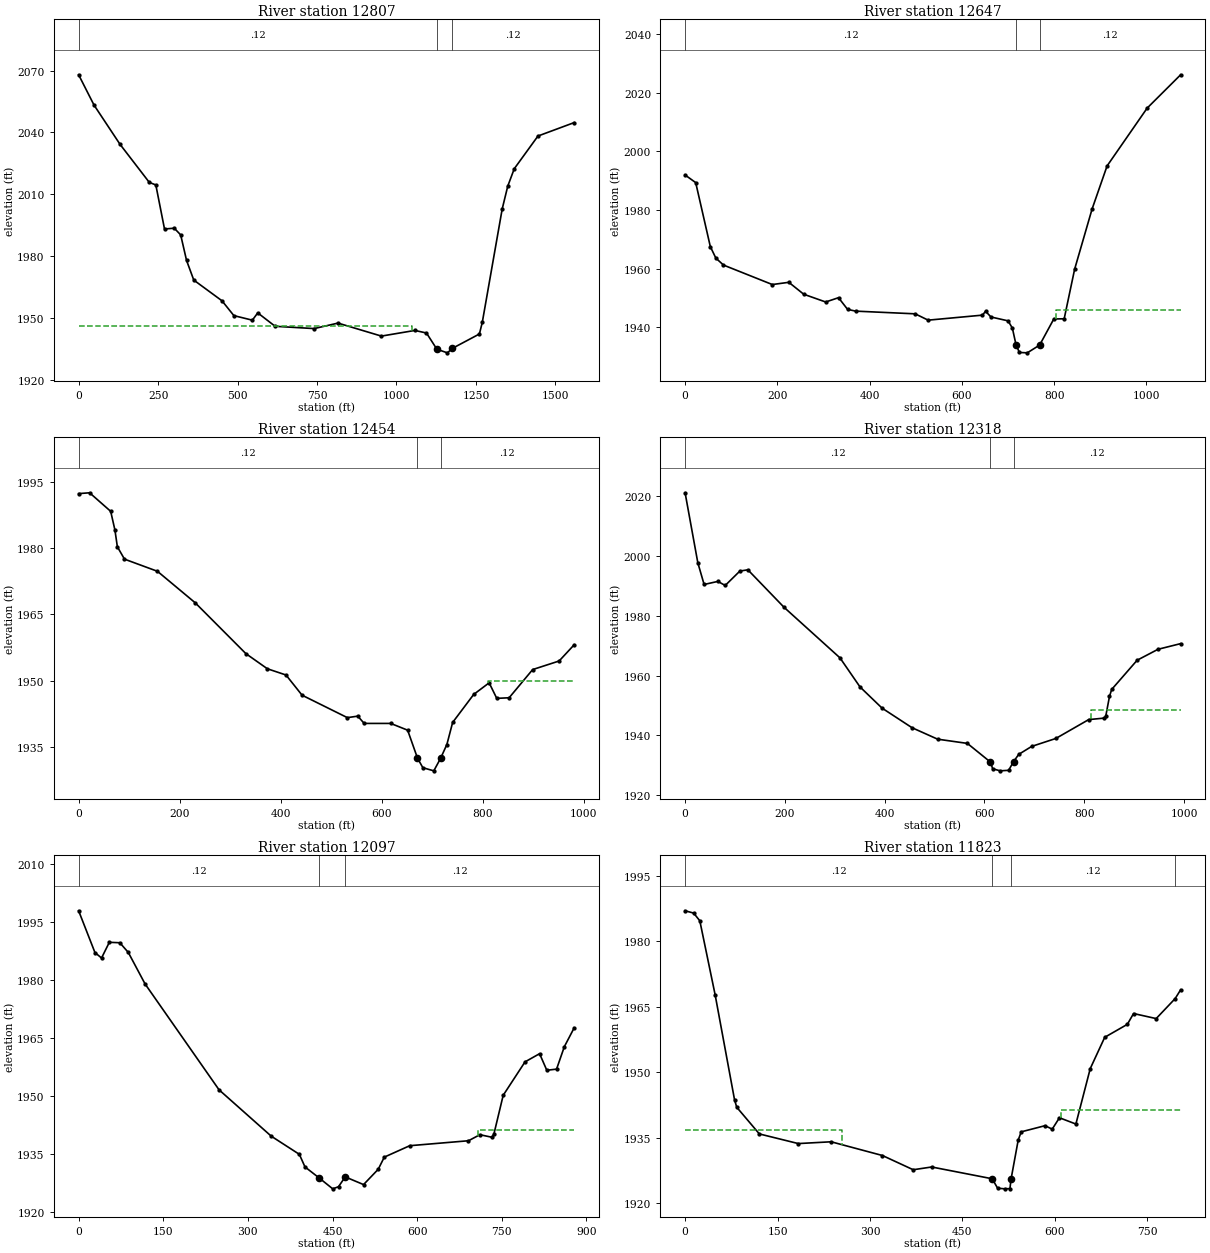
Type RM Length L Ch R = 1 ,12807   ,170.3,160.5,145.5
XS GIS Cut Line= 4
2175549.09993683281030.3620246692176513.63098141281305.815803316
2176507.53689585 281422.911945182176697.65817639281818.486976346
#Sta/Elev= 30
       0 2067.97    48.4 2053.26   130.3 2034.19   222.4 2015.71   242.9 2014.48
   270.2 1993.09   300.9 1993.47   321.1 1990.22   339.6 1977.81   362.3 1968.28
     451 1958.23   488.5 1951.02   546.6 1948.81   563.6 1952.35   618.3 1945.84
     741 1944.73   816.1 1947.39   952.6 1941.08  1058.2 1943.83  1094.5 1942.57
  1127.21934.711  1160.2 1932.95  1176.31935.149    1261  1942.1  1270.1 1947.76
  1332.8 2002.86  1350.2 2013.88  1370.7 2022.35  1445.3 2038.23  1559.2 2044.75
#Mann= 3 ,-1 , 0
       0     .12       0  1127.2     .04       0  1176.3     .12       0
#XS Ineff= 2 , 0
         1050.37 1946.13
Permanent Ineff=
       F       F
Bank Sta=1127.2,1176.3
XS Rating Curve= 0 ,0
Exp/Cntr(USF)=0,0
Exp/Cntr=0.3,0.1

Type RM Length L Ch R = 1 ,12647   ,187.4,192.6,197.6
XS GIS Cut Line= 4
     2175832.543      281152.906     2176333.701      281494.194
      2176492.82      281635.236     2176647.059       281838.79
#Sta/Elev= 30
       0 1991.97      23 1989.37    54.7 1967.51    66.7 1963.59    83.2 1961.22
   189.1 1954.57   224.9 1955.33   257.2 1951.26   304.8 1948.61   332.6 1950.08
   352.3 1946.09   369.8 1945.49   498.8 1944.57     527 1942.41   644.6 1944.12
   651.5 1945.44   663.2 1943.49   700.3 1942.17   709.6 1939.68   717.7 1933.85
   724.9 1931.38   741.9 1931.25   768.7  1933.9   799.4 1942.81   821.9 1942.88
   844.6 1959.83   882.4 1980.35   914.9 1995.06  1001.8 2014.81  1074.4 2026.19
#Mann= 3 ,-1 , 0
       0     .12       0   717.7     .04       0   768.7     .12       0
#XS Ineff= 2 , 0
                           804.5         1945.74
Permanent Ineff=
       F       F
Bank Sta=717.7,768.7
XS Rating Curve= 0 ,0
Exp/Cntr=0.3,0.1

Type RM Length L Ch R = 1 ,12454   ,135.1,136.6,140.9
XS GIS Cut Line= 4
      2175768.93       281263.68     2176243.001      281638.627
     2176336.738      281770.074      2176512.36      281895.057
#Sta/Elev= 30
       0  1992.3    21.7 1992.49    63.5 1988.29    71.9 1984.05    76.7 1980.27
    90.8 1977.47   156.1 1974.72     231 1967.58   331.2 1956.09   373.8 1952.66
   410.7 1951.25   442.5 1946.68   532.2  1941.6   552.9 1941.94   565.5 1940.29
   618.1 1940.29   651.6 1938.76   671.1 1932.43   681.7 1930.27   703.4 1929.56
   716.7 1932.36   729.3 1935.52   740.7 1940.51   782.4 1946.85     813 1949.48
   828.1 1945.96   852.6  1946.1   899.2 1952.48   951.6 1954.42   981.4 1958.09
#Mann= 3 ,-1 , 0
       0     .12       0   671.1     .04       0   716.7     .12       0
#XS Ineff= 2 , 0
                           811.7         1949.92
Permanent Ineff=
       F       F
Bank Sta=671.1,716.7
XS Rating Curve= 0 ,0
Exp/Cntr=0.3,0.1

Type RM Length L Ch R = 1 ,12318   ,229.3,220.5,226.7
XS GIS Cut Line= 4
     2175683.025      281387.939      2176139.23       281709.12
     2176206.018      281837.139     2176463.439      281972.821
#Sta/Elev= 30
       0 2021.07    25.5 1997.69    38.1 1990.43    65.7 1991.45    80.4  1990.1
   109.8 1994.91   125.8 1995.33   198.3  1982.8   310.4  1965.9   350.5  1956.2
   394.7 1949.11   454.8 1942.56   506.1 1938.73   565.7 1937.32     612 1931.07
   616.4 1928.85   631.3 1928.15   648.4 1928.33   658.2 1931.21   668.6 1933.65
   694.5 1936.31     743 1938.97   808.8 1945.27   840.4 1945.78   843.1 1946.48
   850.5 1953.01   854.9 1955.35   905.9 1965.11   947.8 1968.77   993.1 1970.66
#Mann= 3 ,-1 , 0
       0     .12       0     612     .04       0   658.2     .12       0
#XS Ineff= 2 , 0
                           812.9         1948.47
Permanent Ineff=
       F       F
Bank Sta=612,658.2
XS Rating Curve= 0 ,0
Exp/Cntr=0.3,0.1

Type RM Length L Ch R = 1 ,12097   ,288.9,273.9,171.9
XS GIS Cut Line= 4
     2175596.968      281639.284     2175928.465      281818.115
     2176030.553      281936.979     2176356.706      282049.218
#Sta/Elev= 30
       0 1997.93    28.9 1987.14    40.6 1985.72    54.4 1989.78      73 1989.67
      88 1987.17   117.8 1979.01   248.9 1951.65   341.4 1939.67   391.2 1934.98
   401.2 1931.72   426.1  1928.9   450.4 1926.06   460.6 1926.61   472.5 1929.15
     505 1927.16     531 1931.12   541.8 1934.26   586.9 1937.21     691 1938.49
   711.2 1940.05   732.6 1939.39   736.1 1940.26   752.5 1950.24   791.2 1958.88
     817 1960.99   829.8 1956.71   847.1    1957   860.9 1962.81   878.3 1967.67
#Mann= 3 ,-1 , 0
       0     .12       0   426.1     .04       0   472.5     .12       0
#XS Ineff= 2 , 0
                           707.6         1941.23
Permanent Ineff=
       F       F
Bank Sta=426.1,472.5
XS Rating Curve= 0 ,0
Exp/Cntr=0.3,0.1

Type RM Length L Ch R = 1 ,11823   ,129.6,128,129.2
XS GIS Cut Line= 4
     2175549.134      282013.575     2176001.656      282092.227
     2176109.399      282069.601      2176339.97      282113.776
#Sta/Elev= 30
       0    1987    13.9 1986.47    23.9  1984.7    48.7 1967.77    80.2 1943.69
    83.8 1941.95   120.5 1935.83   183.7 1933.62     237 1934.03   320.3 1930.88
   370.2 1927.62   400.2 1928.25   498.4 1925.55   507.2 1923.38   519.2 1923.24
   527.2  1923.3   528.9  1925.4   540.6 1934.43   545.5 1936.31   584.1 1937.72
   595.8 1936.93   607.5 1939.54   634.2  1938.1   657.5 1950.81     681 1957.99
   717.7 1960.96   727.8 1963.44   764.5 1962.28   795.31966.864   804.2 1968.88
#Mann= 4 ,-1 , 0
       0     .12       0   498.4     .04       0   528.9     .12       0
   795.3    .016       0
#XS Ineff= 2 , 0
           254.1 1936.83   609.6          1941.3
Permanent Ineff=
       F       F
Bank Sta=498.4,528.9
XS Rating Curve= 0 ,0
Exp/Cntr=0.3,0.1

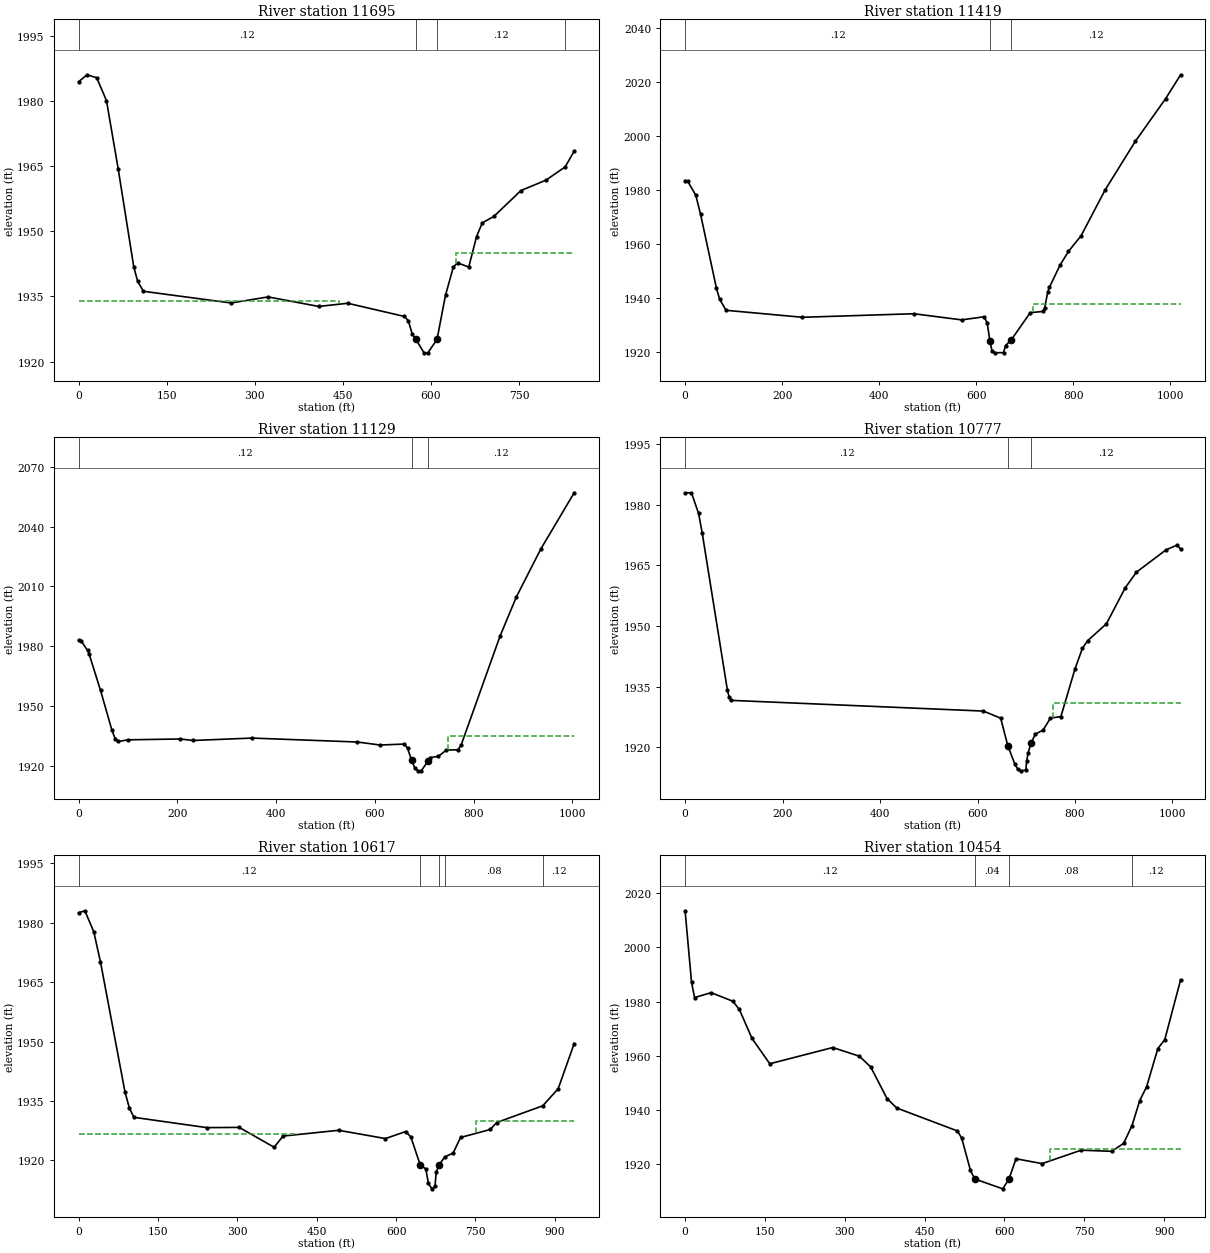
Type RM Length L Ch R = 1 ,11695   ,275.2,276.7,279
XS GIS Cut Line= 4
     2175506.119      282134.778     2176041.298      282213.116
      2176145.53      282194.532     2176342.496      282190.852
#Sta/Elev= 30
       0  1984.4    14.2    1986    30.8 1985.32    47.4 1980.06    67.3  1964.4
    93.8 1941.85   100.4 1938.49   110.4 1936.16   259.6 1933.48   322.6 1934.87
   408.8 1932.68   458.3 1933.41   554.8 1930.37   561.4 1929.38   568.1 1926.29
   574.5 1925.08   588.1    1922   594.7    1922   610.3 1925.11   624.7 1935.27
   638.1 1941.76   645.2  1942.7   664.3 1941.75   677.6 1948.77   687.4 1951.91
   707.1  1953.4   753.1 1959.35   795.7 1961.74  828.511964.803   843.8 1968.43
#Mann= 4 ,-1 , 0
       0     .12       0   574.5     .04       0   610.3     .12       0
  828.51    .016       0
#XS Ineff= 2 , 0
           443.7 1933.86   643.1         1944.87
Permanent Ineff=
       F       F
Bank Sta=574.5,610.3
XS Rating Curve= 0 ,0
Exp/Cntr=0.3,0.1

Type RM Length L Ch R = 1 ,11419   ,287.9,289.9,292.1
XS GIS Cut Line= 4
     2175488.329      282494.756     2175963.273      282488.453
     2176207.148      282470.547     2176509.389      282472.201
#Sta/Elev= 30
       0 1983.38     5.6 1983.09      22 1978.02    31.9 1970.96    64.7 1943.57
    71.2 1939.58    84.4 1935.46   241.8 1932.88   471.5 1934.19   570.2 1931.92
   616.3 1933.06   622.8 1930.93   628.4 1924.24     633 1920.34   639.4 1919.73
   656.7 1919.83   660.7 1922.41   672.2 1924.45   711.7 1934.58   737.9 1935.04
   741.2 1936.16   747.8 1942.24   751.1 1943.96   773.1 1952.13   790.4 1957.21
   816.7 1963.07   865.9 1979.91   928.2  1997.9   990.6 2013.67  1021.8 2022.55
#Mann= 3 ,-1 , 0
       0     .12       0   628.4     .04       0   672.2     .12       0
#XS Ineff= 2 , 0
                           716.7         1937.72
Permanent Ineff=
       F       F
Bank Sta=628.4,672.2
XS Rating Curve= 0 ,0
Exp/Cntr=0.3,0.1

Type RM Length L Ch R = 1 ,11129   ,336.2,352.2,363.8
XS GIS Cut Line= 4
     2175472.625       282711.38     2176002.416      282757.099
     2176222.608      282766.348     2176473.666      282784.919
#Sta/Elev= 30
       0 1982.95     4.9 1982.62    18.1 1977.82    21.4 1975.87    44.4  1957.7
    67.5 1937.68    74.1 1933.48    80.7  1932.1   100.4 1932.91   205.7 1933.34
   232.1 1932.58   351.4 1933.79   564.8 1931.81   610.6  1930.3   659.9 1930.78
   666.4  1928.7   674.5  1922.6   681.3 1918.64   687.7 1917.34     694 1917.34
   708.4 1922.44   712.4 1924.01   728.8 1924.63   745.2  1927.8   768.3 1927.88
   774.8 1930.23   853.8 1985.04   886.7  2004.6     936 2028.59  1003.9 2056.94
#Mann= 3 ,-1 , 0
       0     .12       0   674.5     .04       0   708.4     .12       0
#XS Ineff= 2 , 0
                           747.9         1934.75
Permanent Ineff=
       F       F
Bank Sta=674.5,708.4
XS Rating Curve= 0 ,0
Exp/Cntr=0.3,0.1

Type RM Length L Ch R = 1 ,10777   ,153.9,160,168.5
XS GIS Cut Line= 5
     2175459.389      282771.676     2175975.261      283034.977
     2176121.602      283133.266     2176340.309      283263.133
     2176333.522      283260.852
#Sta/Elev= 30
       0 1982.96      13 1982.96    27.7 1977.84    35.1 1973.01    86.7 1934.23
    90.4 1932.41      94 1931.63     612 1928.98   647.5 1927.22   662.1  1920.4
   676.3 1915.94   682.7 1914.55   689.9  1914.2   699.1  1914.4   700.9 1916.64
   703.6 1918.53   709.4 1920.98   718.7 1923.27   734.5 1924.29   749.6 1927.24
     771 1927.61   799.8 1939.36   815.3 1944.53   826.1  1946.4   864.4 1950.56
   903.1 1959.48     926 1963.33     987 1968.87  1009.8 1970.04  1016.7    1969
#Mann= 3 ,-1 , 0
       0     .12       0   662.1     .04       0   709.4     .12       0
#XS Ineff= 2 , 0
                           753.9         1931.02
Permanent Ineff=
       F       F
Bank Sta=662.1,709.4
XS Rating Curve= 0 ,0
Exp/Cntr=0.3,0.1

Type RM Length L Ch R = 1 ,10617   ,165.9,162.8,162.7
XS GIS Cut Line= 4
     2175458.475      282797.211     2175936.814      283181.296
      2176009.86      283279.477      2176166.95      283404.363
#Sta/Elev= 30
       0 1982.54    11.8 1983.03    28.6 1977.74    41.3 1970.11    87.6 1937.29
    95.8 1933.29   104.4 1930.89   242.4 1928.29   303.5 1928.35   369.5 1923.33
   386.3 1926.16   491.5 1927.62   579.8 1925.53   618.3 1927.31     628 1925.89
   645.3 1918.96   656.1 1917.85   661.1 1914.19   667.6 1912.84   673.5 1913.48
   675.7 1917.07   681.3 1918.95  692.091920.907   707.7 1921.86   721.8  1925.8
   777.9 1927.82   789.9 1929.57  877.111933.807   906.3 1938.12   936.5 1949.51
#Mann= 5 ,-1 , 0
       0     .12       0   645.3     .04       0   681.3     .12       0
  692.09     .08       0  877.11     .12       0
#XS Ineff= 2 , 0
           412.5 1926.76   750.9         1929.95
Permanent Ineff=
       F       F
Bank Sta=645.3,681.3
XS Rating Curve= 0 ,0
Exp/Cntr=0.3,0.1

Type RM Length L Ch R = 1 ,10454   ,286.9,281,279.2
XS GIS Cut Line= 3
     2175395.594      282943.625      2175757.76      283211.581
     2176043.177      283598.018
#Sta/Elev= 30
       0 2013.53    12.1 1987.11    17.8  1981.5    48.9 1983.31    89.7 1980.14
   101.9  1977.1   125.7 1966.42   159.1 1957.07   277.4 1963.06   327.5 1959.85
   348.6 1955.91   379.4 1944.21   397.7 1940.73   511.5 1932.28   519.7 1929.59
     536 1917.75   544.1 1914.57   596.6 1910.91   608.4 1914.49   621.6 1922.01
   670.6 1920.22     744 1925.18   801.1 1924.76   823.7 1927.66  839.611934.277
   854.1  1943.5     867  1948.6   888.1 1962.69   901.1 1965.99   930.9  1988.1
#Mann= 4 ,-1 , 0
       0     .12       0   544.1     .04       0   608.4     .08       0
  839.61     .12       0
#XS Ineff= 2 , 0
                           686.4         1925.59
Permanent Ineff=
       F       F
Bank Sta=544.1,608.4
XS Rating Curve= 0 ,0
Exp/Cntr=0.3,0.1

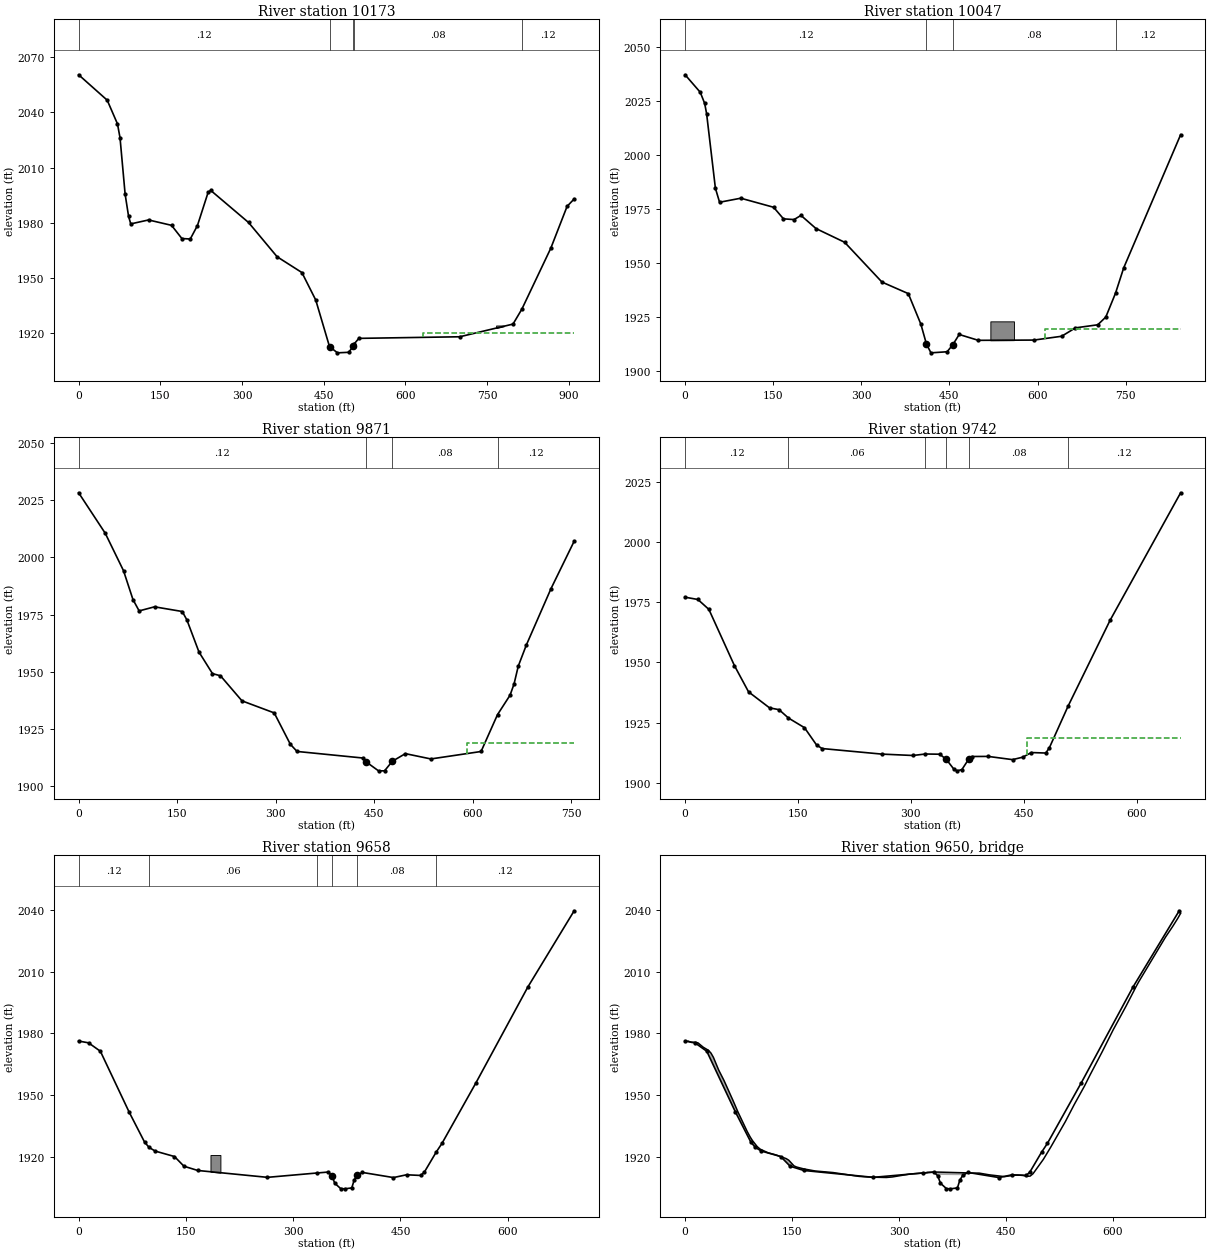
Type RM Length L Ch R = 1 ,10173   ,127.4,126.1,125.8
XS GIS Cut Line= 3
     2175213.556      283182.126     2175579.327      283452.748
     2175945.098      283723.371
#Sta/Elev= 30
       0  2060.5    52.5 2046.65    71.3 2033.77      76 2026.25    85.4 1995.42
    91.7 1983.44    95.7 1979.29   128.4 1981.44   170.6 1978.51   189.6 1971.32
     205 1971.06   218.2 1978.41   237.8 1996.48   242.7  1997.5     312 1980.07
   364.5 1961.39     410  1952.8   435.4 1937.85   460.7 1912.47   475.3 1909.07
   495.9 1909.36   504.1 1912.55  506.111913.973   514.6 1916.95   699.8 1917.82
   797.7 1924.73  813.961932.875   867.1 1966.06     897 1988.85     910 1992.88
#Mann= 5 ,-1 , 0
       0     .12       0   460.7     .04       0   504.1     .12       0
  506.11     .08       0  813.96     .12       0
#XS Ineff= 2 , 0
                           632.1         1920.13
Permanent Ineff=
       F       F
#Block Obstruct= 1 ,-1
  766.61   780.8 1923.96
Bank Sta=460.7,504.1
XS Rating Curve= 0 ,0
Exp/Cntr=0.3,0.1

Type RM Length L Ch R = 1 ,10047   ,177,175.2,177.6
XS GIS Cut Line= 4
     2175169.031      283310.023     2175478.466      283534.195
      2175561.95      283596.035     2175851.696      283806.181
#Sta/Elev= 30
       0 2036.94    25.8 2028.86    33.3 2023.73    36.6 2019.02    51.6  1984.5
    58.7 1978.04    94.8 1979.91   150.7 1975.72   167.5 1970.37   185.5 1970.04
   197.3 1971.96   222.9 1965.88   271.6 1959.55   335.2 1941.15     380 1935.83
   401.4 1921.73   410.9 1912.52   418.6 1908.46   446.1 1908.96   455.6 1912.13
   466.7 1916.94   499.2 1914.24   594.1 1914.36   641.1 1916.12   664.6    1920
   702.6 1921.42   716.3    1925  732.83 1936.03   746.8 1947.75   843.7 2009.25
#Mann= 4 ,-1 , 0
       0     .12       0   410.9     .04       0   455.6     .08       0
  732.83     .12       0
#XS Ineff= 2 , 0
                           613.3         1919.33
Permanent Ineff=
       F       F
#Block Obstruct= 1 ,-1
  519.75  559.88 1923.01
Bank Sta=410.9,455.6
XS Rating Curve= 0 ,0
Exp/Cntr=0.3,0.1

Type RM Length L Ch R = 1 ,9871    ,140.1,129.7,127.8
XS GIS Cut Line= 5
     2175035.145      283423.309     2175353.755      283659.936
     2175400.895      283693.916     2175449.607      283730.022
      2175596.05      283918.412
#Sta/Elev= 30
       0 2028.26    40.5 2010.56    68.3 1994.19    82.7 1981.56    92.1  1976.6
   115.5 1978.39   157.7 1976.34   164.8 1972.64   183.2  1958.6   203.7 1949.18
   215.9 1948.23   248.6 1937.27   297.7 1931.99   322.2 1918.29   332.4 1915.14
   432.2 1912.28   436.9 1910.72   456.4 1906.66   465.6 1906.66   477.4 1910.84
   497.3 1914.18   536.1 1911.86   612.5 1915.12  637.531931.242   656.6 1939.73
   662.7 1944.65   669.1 1952.44   681.5 1961.75   718.9 1986.32   754.2 2007.08
#Mann= 4 ,-1 , 0
       0     .12       0   436.9     .04       0   477.4     .08       0
  637.53     .12       0
#XS Ineff= 2 , 0
                           590.8         1918.77
Permanent Ineff=
       F       F
Bank Sta=436.9,477.4
XS Rating Curve= 0 ,0
Exp/Cntr=0.3,0.1

Type RM Length L Ch R = 1 ,9742    ,81,83.5,84.1
XS GIS Cut Line= 4
     2175018.437      283644.407     2175313.895      283793.854
      2175363.71      283821.911     2175594.465      283962.196
#Sta/Elev= 30
       0 1977.06      17 1976.11    31.6    1972    65.6 1948.62    84.3 1937.77
   112.2 1931.12   124.8 1930.38  137.321926.902   158.6  1922.9   174.6 1915.74
   181.9 1914.25   261.2 1911.94   302.7 1911.36  319.271911.978   338.2 1911.89
   346.8 1909.82   357.3 1905.59   361.4 1904.99   367.7 1905.51   376.9 1909.91
   381.1 1910.94   402.5 1910.98     435 1909.64   448.5 1910.66     460 1912.58
   479.2 1912.38     484 1914.63  508.881931.911   564.6 1967.49   658.3  2020.4
#Mann= 6 ,-1 , 0
       0     .12       0  137.32     .06       0  319.27     .08       0
   346.8     .04       0   376.9     .08       0  508.88     .12       0
#XS Ineff= 2 , 0
                           453.7         1918.58
Permanent Ineff=
       F       F
Bank Sta=346.8,376.9
XS Rating Curve= 0 ,0
Exp/Cntr=0.5,0.3

Type RM Length L Ch R = 1 ,9658    ,26.1,26.3,27.5
BEGIN DESCRIPTION:
Merged DS Survey DRC062BU
END DESCRIPTION:
XS GIS Cut Line= 4
     2174977.783      283718.959     2175284.406      283868.921
     2175325.117      283898.295      2175598.76      284024.552
#Sta/Elev= 30
       0 1976.32    13.8 1975.47    30.4 1971.37    70.6 1941.81    92.3 1927.13
   98.66 1924.58   107.1 1922.83     134 1920.19   147.3 1915.47   166.5 1913.41
     264 1910.07  333.51 1912.19   348.9 1912.64   354.2 1910.86   358.1 1907.22
   366.4  1904.6     372 1904.48   381.9 1904.92   385.3 1908.75   389.3 1910.98
   396.6 1912.46   440.2 1909.96   458.5 1911.31   478.3 1910.99   483.3 1912.54
  499.931922.316     508 1926.54   555.8 1956.17     628 2002.53   692.9 2039.66
#Mann= 6 ,-1 , 0
       0     .12       0   98.66     .06       0  333.51     .08       0
   354.2    .035       0   389.3     .08       0  499.93     .12       0
#XS Ineff= 2 , 0
             345 1911.53     400         1911.96
Permanent Ineff=
       F       F
#Block Obstruct= 1 ,-1
  184.35  198.24 1920.93
Bank Sta=354.2,389.3
XS Rating Curve= 0 ,0
Exp/Cntr=0.5,0.3

Type RM Length L Ch R = 3 ,9650    ,,,
BEGIN DESCRIPTION:
Merged DS Survey DRC060RP
Unnamed Rd
END DESCRIPTION:
Bridge Culvert--1,0,-1,-1, 0
Deck Dist Width WeirC Skew NumUp NumDn MinLoCord MaxHiCord MaxSubmerge Is_Ogee
7,10,2.6,0, 60, 60, , , 0.98, 0, 0,0,,
     4.2       9    14.5    18.1    25.4    32.7    36.3    39.7    47.1    54.5
    66.8    74.2    87.2    91.4    94.5   101.2   105.4   116.3   127.2   141.8
   145.4   152.7   156.4   166.2   182.4   207.3   243.9   261.1   282.2   290.6
   315.2  339.08  339.18   354.3  400.13  400.23   412.4   426.2     448   458.9
   466.1   473.4   480.6   483.9   487.9   502.4   512.7   533.2   545.5   560.2
   567.6     585   600.2   618.4   632.9   636.5   673.7   683.6   690.9   694.9
 1976.29 1975.67 1975.75 1975.43 1973.34 1971.82 1970.47 1968.41 1962.23 1957.19
 1947.73 1941.79 1932.29 1929.61 1927.93 1924.98 1923.75 1922.02 1920.99 1919.17
 1918.39 1915.64 1915.08 1914.19 1913.16 1912.41 1910.53 1910.15    1910 1910.25
 1911.68 1912.31 1912.45 1912.63  1912.2 1912.16 1912.13 1911.31 1910.42    1911
 1911.16 1911.05  1910.6 1910.68 1911.83 1918.82 1924.73 1937.14 1945.33 1954.54
 1959.66 1971.19 1981.72 1993.36 2003.11 2005.36 2026.87 2031.97 2035.99 2038.43
                                                                                
                                                                                
                                                                                
                 1911.24 1911.24 1911.04
                                                                                
                                                                                
     6.2      11    16.5    20.1    27.4    34.7    38.3    41.7    49.1    56.5
    68.8    76.2    89.2    93.4    96.5   103.2   107.4   118.3   129.2   143.8
   147.4   154.7   158.4   168.2   184.4   209.3   245.9   263.1   284.2   292.6
   317.2  341.08  341.18   356.3  402.13  402.23   414.4   428.2     450   460.9
   468.1   475.4   482.6   485.9   489.9   504.4   514.7   535.2   547.5   562.2
   569.6     587   602.2   620.4   634.9   638.5   675.7   685.6   692.9   696.9
 1976.29 1975.67 1975.75 1975.43 1973.34 1971.82 1970.47 1968.41 1962.23 1957.19
 1947.73 1941.79 1932.29 1929.61 1927.93 1924.98 1923.75 1922.02 1920.99 1919.17
 1918.39 1915.64 1915.08 1914.19 1913.16 1912.41 1910.53 1910.15    1910 1910.25
 1911.68 1912.31 1912.45 1912.63  1912.2 1912.16 1912.13 1911.31 1910.42    1911
 1911.16 1911.05  1910.6 1910.68 1911.83 1918.82 1924.73 1937.14 1945.33 1954.54
 1959.66 1971.19 1981.72 1993.36 2003.11 2005.36 2026.87 2031.97 2035.99 2038.43
                                                                                
                                                                                
                                                                                
                 1910.93 1910.93  1910.8
                                                                                
                                                                                
BR Coef=-1 , 1 , 0 ,, 0 ,,,0.8,0,1.2,0,
WSPro=,,,, 1 ,,,, 0 ,,,, 0 ,,,,-1 ,-1 ,-1 , 0 , 0 , 0 , 0 , 0
BC Design=,, 0 ,, 0 ,,0,,,,
BC HTab HWMax=0
BC HTab TWMax=0
BC HTab MaxFlow=0
BC Use User HTab Curves=0
BC User HTab FreeFlow(D)= 0

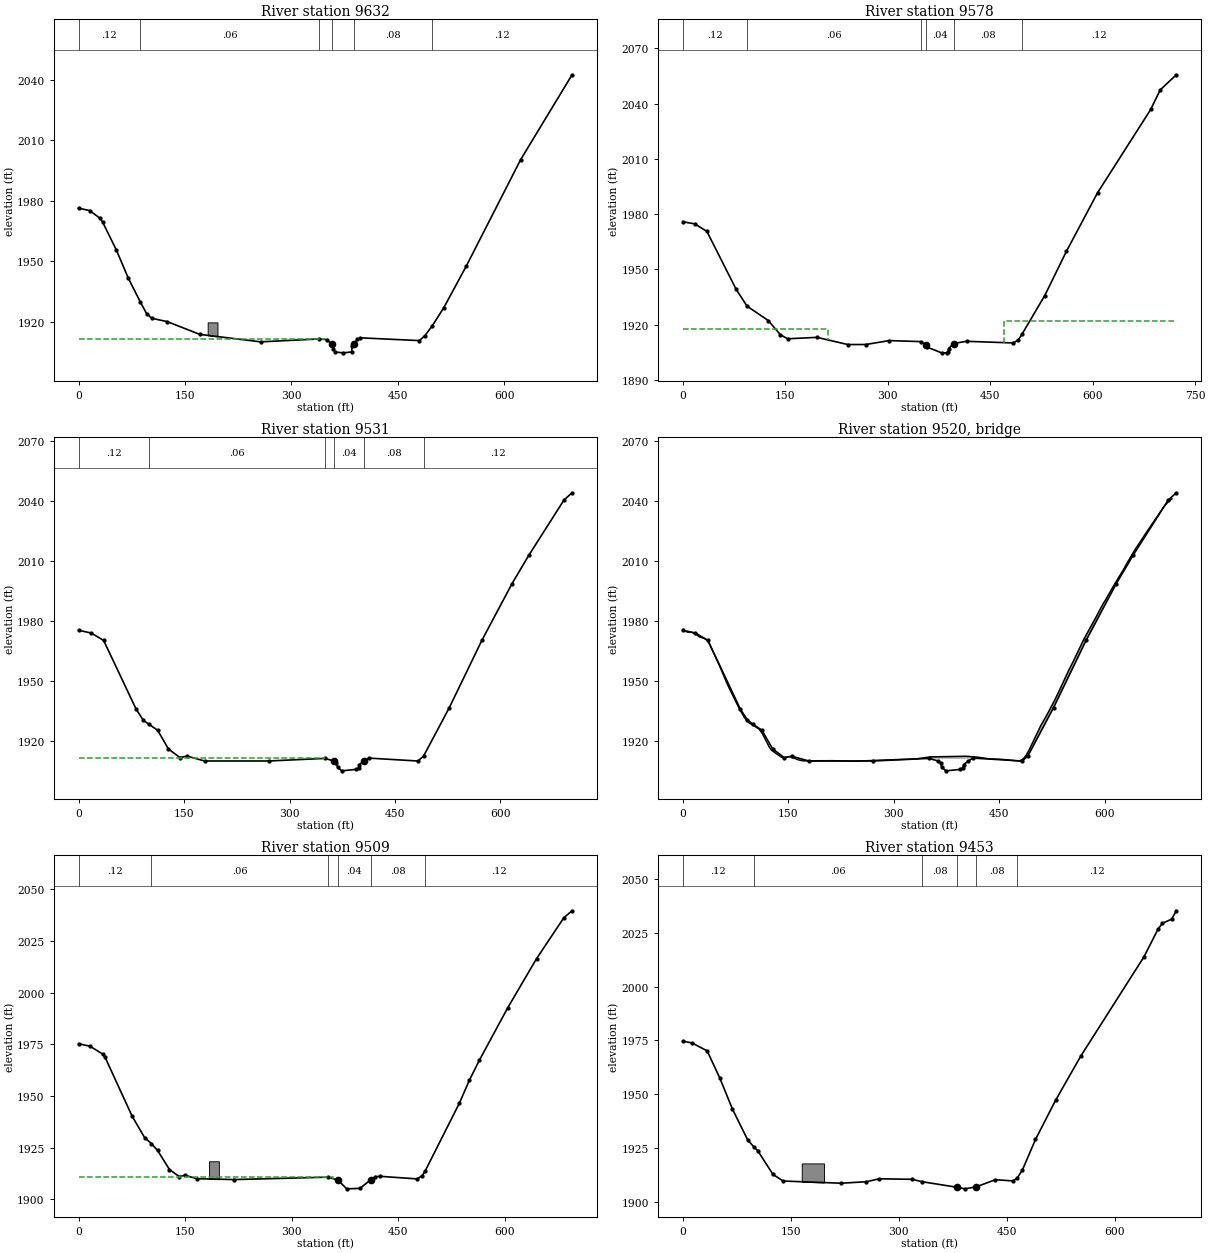
Type RM Length L Ch R = 1 ,9632    ,66.7,53.7,43.8
BEGIN DESCRIPTION:
Merged US Survey DRC058BD
END DESCRIPTION:
XS GIS Cut Line= 4
     2174964.899      283741.634     2175273.584      283892.626
     2175317.387      283924.577     2175585.876      284052.895
#Sta/Elev= 30
       0 1976.24    15.5 1975.05    30.1 1971.28    33.8 1969.43    53.1 1955.62
    70.3 1941.37   86.971929.787    95.9 1923.92   103.2 1921.62   125.1 1919.95
   170.8 1913.65   256.4 1909.94  338.511911.357   349.6 1911.06   356.5 1908.83
   358.8 1906.16   361.9 1904.86   373.2 1904.49   384.9 1904.95   385.3  1907.8
   388.6 1909.04     393 1911.27   396.5 1911.94   480.1 1910.56   488.1 1913.02
  498.441917.939   514.6 1926.89   546.3 1947.51   622.8 2000.25   695.3 2042.37
#Mann= 6 ,-1 , 0
       0     .12       0   86.97     .06       0  338.51     .08       0
   356.5    .035       0   388.6     .08       0  498.44     .12       0
#XS Ineff= 2 , 0
          347.17  1911.4     395          1911.4
Permanent Ineff=
       F       F
#Block Obstruct= 1 ,-1
  181.94  195.73  1919.6
Bank Sta=356.5,388.6
XS Rating Curve= 0 ,0
Exp/Cntr=0.5,0.3

Type RM Length L Ch R = 1 ,9578    ,56.8,47.3,38.7
XS GIS Cut Line= 4
     2174925.204      283819.498     2175242.692      283948.076
     2175314.904      283971.896     2175597.706      284083.115
#Sta/Elev= 30
       0 1975.86    17.7 1974.71    35.3 1970.63    78.1 1939.23   94.121930.055
   125.1  1922.3   142.8 1914.62   153.4 1912.39   196.5 1913.15   241.7 1909.25
     268 1909.28   302.1 1911.41  349.01 1910.85   355.6 1909.02   358.2 1907.78
   378.9 1904.76   386.8 1904.76   388.4 1905.31   389.3 1907.08   396.4 1909.82
   415.4 1911.02   483.8 1910.12   491.1 1911.72  496.591914.867   529.9 1935.83
   561.6 1959.81   607.4 1991.72     685 2036.76   698.9 2047.36   722.5 2055.59
#Mann= 6 ,-1 , 0
       0     .12       0   94.12     .06       0  349.01     .08       0
   355.6     .04       0   396.4     .08       0  496.59     .12       0
#XS Ineff= 2 , 0
           212.1 1917.59   469.9         1922.09
Permanent Ineff=
       F       F
Bank Sta=355.6,396.4
XS Rating Curve= 0 ,0
Exp/Cntr=0.5,0.3

Type RM Length L Ch R = 1 ,9531    ,21.5,21.9,20
BEGIN DESCRIPTION:
Merged DS Survey DRC052BU
END DESCRIPTION:
XS GIS Cut Line= 4
     2174902.695      283881.208     2175224.729      284000.597
     2175297.776       284006.88     2175564.829      284106.632
#Sta/Elev= 30
       0 1975.39      18 1974.01    35.7  1970.3    81.8 1935.95      92 1930.39
   99.741928.382   112.5 1925.32   127.8 1915.99   144.2 1911.63   154.7 1912.35
   179.2 1909.93   270.2 1909.93  350.371911.226   363.2 1909.91   366.7 1908.88
   368.3 1906.84   374.3    1905   394.1  1905.7   398.4 1906.49   399.3 1908.11
   405.7 1909.86   412.8 1911.38   482.6 1909.92  490.661912.394   527.3 1936.68
   573.6 1970.38   616.5 1998.77   640.2 2012.87   690.4 2040.64   701.8 2044.23
#Mann= 6 ,-1 , 0
       0     .12       0   99.74     .06       0  350.37     .08       0
   363.2     .04       0   405.7     .08       0  490.66     .12       0
#XS Ineff= 2 , 0
           349.9 1911.26   414.5          1911.3
Permanent Ineff=
       F       F
Bank Sta=363.2,405.7
XS Rating Curve= 0 ,0
Exp/Cntr=0.5,0.3

Type RM Length L Ch R = 3 ,9520    ,,,
BEGIN DESCRIPTION:
Merged DS Survey DRC050RP
Unnamed Rd
END DESCRIPTION:
Bridge Culvert--1,0,-1,-1, 0
Deck Dist Width WeirC Skew NumUp NumDn MinLoCord MaxHiCord MaxSubmerge Is_Ogee
10,10,2.6,0, 60, 60, , , 0.98, 0, 0,0,,
       0     7.1      11    16.2    23.8    31.5      35    38.5      52    62.2
    66.5    80.4    87.4    90.9    94.4   108.4   113.3   123.5   125.9   129.4
   139.9   143.4   150.3   153.8   164.3   171.3   213.2   243.7   332.1  352.44
  352.54  402.93  419.82  419.92   435.9   454.7     478   482.2   485.1   486.8
   488.6   492.6   509.6   516.7     528   535.1   548.3   555.4   570.6     587
   597.5   601.3   611.2   626.5   632.6   643.2     662   684.9     690   695.6
 1975.29 1974.45 1974.46 1973.98 1972.06 1971.19 1970.19 1968.15 1957.87  1949.3
 1946.03 1936.11 1931.83 1930.22 1928.98 1925.98 1923.58  1916.6 1915.46  1914.5
 1911.93 1911.34 1912.06 1911.93 1910.51 1910.01 1910.09 1909.83    1911 1911.99
 1911.99 1912.32 1911.82 1911.82    1911 1910.72 1909.89 1910.51 1911.36 1912.14
 1912.99 1915.54 1928.02  1932.3 1939.81 1944.94 1954.99 1959.92  1971.1 1981.57
 1988.55 1990.65  1996.8 2005.69 2009.55 2015.82 2025.83 2037.65 2039.54 2041.18
                                                                                
                                                                                
                                                                                
 1911.03 1911.03 1911.03
                                                                                
                                                                                
       6    13.1      17    22.2    29.8    37.5      41    44.5      58    68.2
    72.5    86.4    93.4    96.9   100.4   114.4   119.3   129.5   131.9   135.4
   145.9   149.4   156.3   159.8   170.3   177.3   219.2   249.7   338.1  358.44
  358.54  408.93  425.82  425.92   441.9   460.7     484   488.2   491.1   492.8
   494.6   498.6   515.6   522.7     534   541.1   554.3   561.4   576.6     593
   603.5   607.3   617.2   632.5   638.6   649.2     668   690.9     696   701.6
 1975.29 1974.45 1974.46 1973.98 1972.06 1971.19 1970.19 1968.15 1957.87  1949.3
 1946.03 1936.11 1931.83 1930.22 1928.98 1925.98 1923.58  1916.6 1915.46  1914.5
 1911.93 1911.34 1912.06 1911.93 1910.51 1910.01 1910.09 1909.83    1911 1911.99
 1911.99 1912.32 1911.82 1911.82    1911 1910.72 1909.89 1910.51 1911.36 1912.14
 1912.99 1915.54 1928.02  1932.3 1939.81 1944.94 1954.99 1959.92  1971.1 1981.57
 1988.55 1990.65  1996.8 2005.69 2009.55 2015.82 2025.83 2037.65 2039.54 2041.18
                                                                                
                                                                                
                                                                                
 1911.03 1911.03 1911.03
                                                                                
                                                                                
BR Coef=-1 , 1 , 0 ,, 0 ,,,0.8,0,1.2,0,
WSPro=,,,, 1 ,,,, 0 ,,,, 0 ,,,,-1 ,-1 ,-1 , 0 , 0 , 0 , 0 , 0
BC Design=,, 0 ,, 0 ,,0,,,,
BC HTab HWMax=0
BC HTab TWMax=0
BC HTab MaxFlow=0
BC Use User HTab Curves=0
BC User HTab FreeFlow(D)= 0

Type RM Length L Ch R = 1 ,9509    ,42.8,56.3,64.4
BEGIN DESCRIPTION:
Merged US Survey DRC048BD
END DESCRIPTION:
XS GIS Cut Line= 4
     2174894.281      283901.533     2175224.169      284023.278
     2175297.216      284027.991     2175550.131      284122.244
#Sta/Elev= 30
       0 1975.23    16.1 1974.05    34.6 1970.11    37.1 1968.89    75.5 1940.12
      93 1929.81  102.651926.918   111.3 1923.56     128 1914.34     142 1910.88
   149.6 1911.59   166.5 1909.93   218.9 1909.49  351.641910.654     365 1909.23
   377.6    1905   396.1 1905.23     411  1909.3   417.6 1910.84   424.1 1911.07
   476.6 1909.81   483.6 1911.31  487.651913.451   536.1 1946.48   550.1 1957.51
   564.1 1967.17   603.9 1992.49   644.7 2016.42   683.2 2036.26   694.7  2039.6
#Mann= 6 ,-1 , 0
       0     .12       0  102.65     .06       0  351.64     .08       0
     365     .04       0     411     .08       0  487.65     .12       0
#XS Ineff= 2 , 0
           358.2 1910.57   421.6          1910.8
Permanent Ineff=
       F       F
#Block Obstruct= 1 ,-1
  183.75  197.52 1918.34
Bank Sta=365,411
XS Rating Curve= 0 ,0
Exp/Cntr=0.5,0.3

Type RM Length L Ch R = 1 ,9453    ,155.4,180,178.6
BEGIN DESCRIPTION:
Channel Section burnt based on Effective FIS study
END DESCRIPTION:
XS GIS Cut Line= 4
     2174888.317      283939.649     2175207.303      284063.576
     2175337.814      284110.911      2175529.59      284182.747
#Sta/Elev= 30
       0 1974.67    12.6 1973.84    33.8 1970.17    51.4 1957.55      69 1943.09
    90.1 1928.81   98.771925.487   104.2 1923.73   125.3 1912.72   139.4 1909.63
   220.3 1908.62   255.1 1909.31   273.1 1910.67   318.5 1910.44  332.911909.289
   381.1 1906.73   392.3    1906   407.9 1906.95   434.2 1910.23   458.7  1909.7
  464.571910.944   471.9 1914.74   490.1 1928.94   518.1  1947.2   553.2  1967.8
   640.8 2013.83   660.5 2026.78   666.6 2029.47   679.3 2031.38   685.8 2035.27
#Mann= 6 ,-1 , 0
       0     .12       0   98.77     .06       0  332.91     .08       0
   381.1     .04       0   407.9     .08       0  464.57     .12       0
#Block Obstruct= 1 ,-1
   165.3   196.2 1917.82
Bank Sta=381.1,407.9
XS Rating Curve= 0 ,0
Exp/Cntr=0.5,0.3