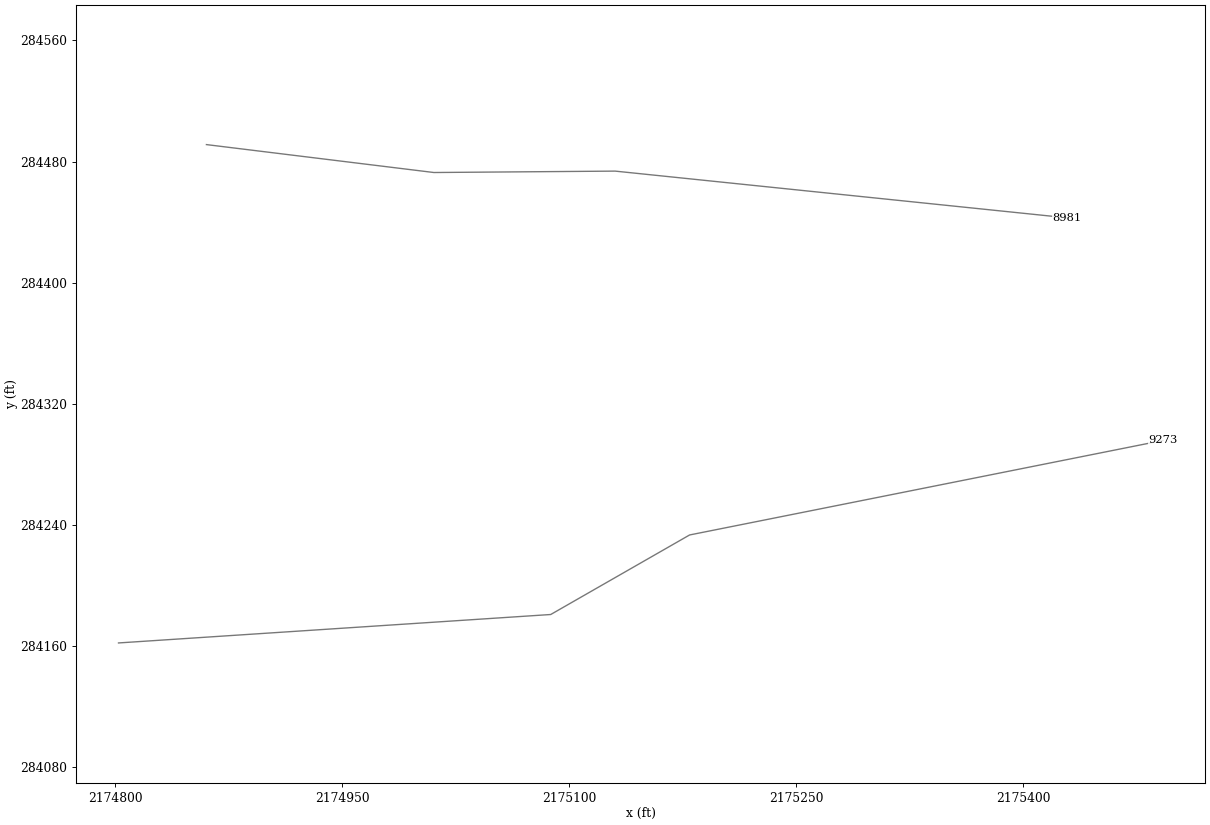
HEC-RAS study DRYCK1.prj: DRYCK1

--- DRYCK1.g01 (geometry) --- (continued)

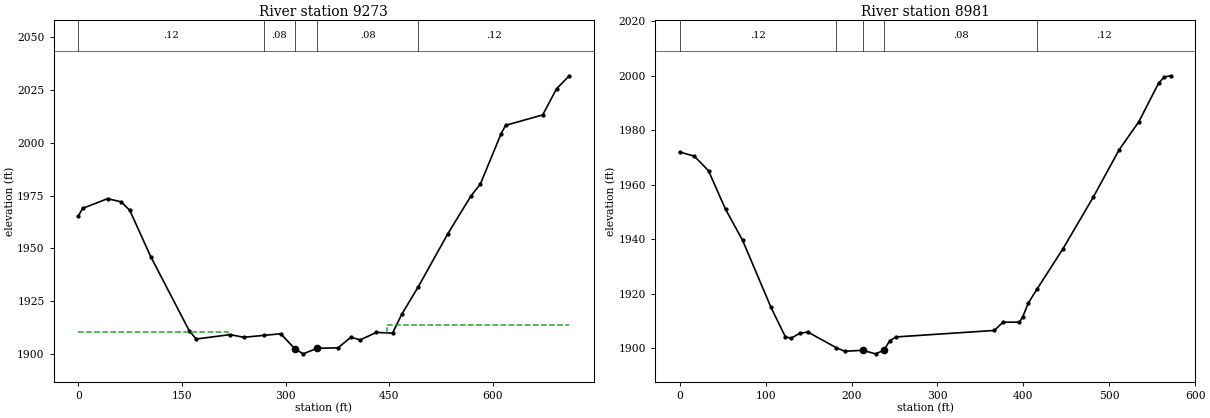
Type RM Length L Ch R = 1 ,9273    ,293.8,291.7,259.7
XS GIS Cut Line= 4
     2174802.185      284161.928      2175087.76      284180.718
     2175179.521      284233.273     2175492.365      284295.747
#Sta/Elev= 30
       0 1965.39     6.1 1968.94    42.2 1973.53      62 1972.04    74.4 1967.99
   104.7  1946.1   160.6 1910.89   170.5 1907.02   219.8  1909.1   239.5 1907.84
  268.851908.741     293 1909.51   313.2 1902.46   325.5 1899.99   345.9 1902.64
     376 1902.84   394.7 1907.88   408.1 1906.59   431.5 1910.16   454.9 1909.79
   468.3 1918.72  492.171931.759     535  1956.9   568.7 1974.92   582.1 1980.43
   612.2 2004.38   618.8 2008.32   672.4 2013.24   692.5 2025.64   710.9 2031.79
#Mann= 5 ,-1 , 0
       0     .12       0  268.85     .08       0   313.2     .04       0
   345.9     .08       0  492.17     .12       0
#XS Ineff= 2 , 0
           216.7 1910.23   446.4          1913.5
Permanent Ineff=
       F       F
Bank Sta=313.2,345.9
XS Rating Curve= 0 ,0
Exp/Cntr=0.3,0.1

Type RM Length L Ch R = 1 ,8981    ,259.9,251.4,242.4
XS GIS Cut Line= 4
     2174860.283      284491.202      2175010.55      284472.756
     2175130.318      284473.681     2175429.059      284442.821
#Sta/Elev= 30
       0 1972.02      17  1970.5    33.5 1965.15    53.3 1950.99    73.2 1939.57
   106.2 1914.95   122.8 1904.22   129.4 1903.52   139.6  1905.4   149.2 1905.86
  181.891900.168   191.9  1898.8   212.9 1899.15     228 1897.86   237.8 1899.19
   244.4 1902.65   251.9 1904.07   366.3 1906.46   376.2 1909.47   395.4 1909.52
   399.2  1911.4   405.8  1916.5  416.021921.673   446.3 1936.54   481.7 1955.59
   511.4 1972.77   534.5 1983.16   557.6  1997.4   564.2 1999.59   571.5 2000.04
#Mann= 5 ,-1 , 0
       0     .12       0  181.89     .08       0   212.9     .04       0
   237.8     .08       0  416.02     .12       0
Bank Sta=212.9,237.8
XS Rating Curve= 0 ,0
Exp/Cntr=0.3,0.1