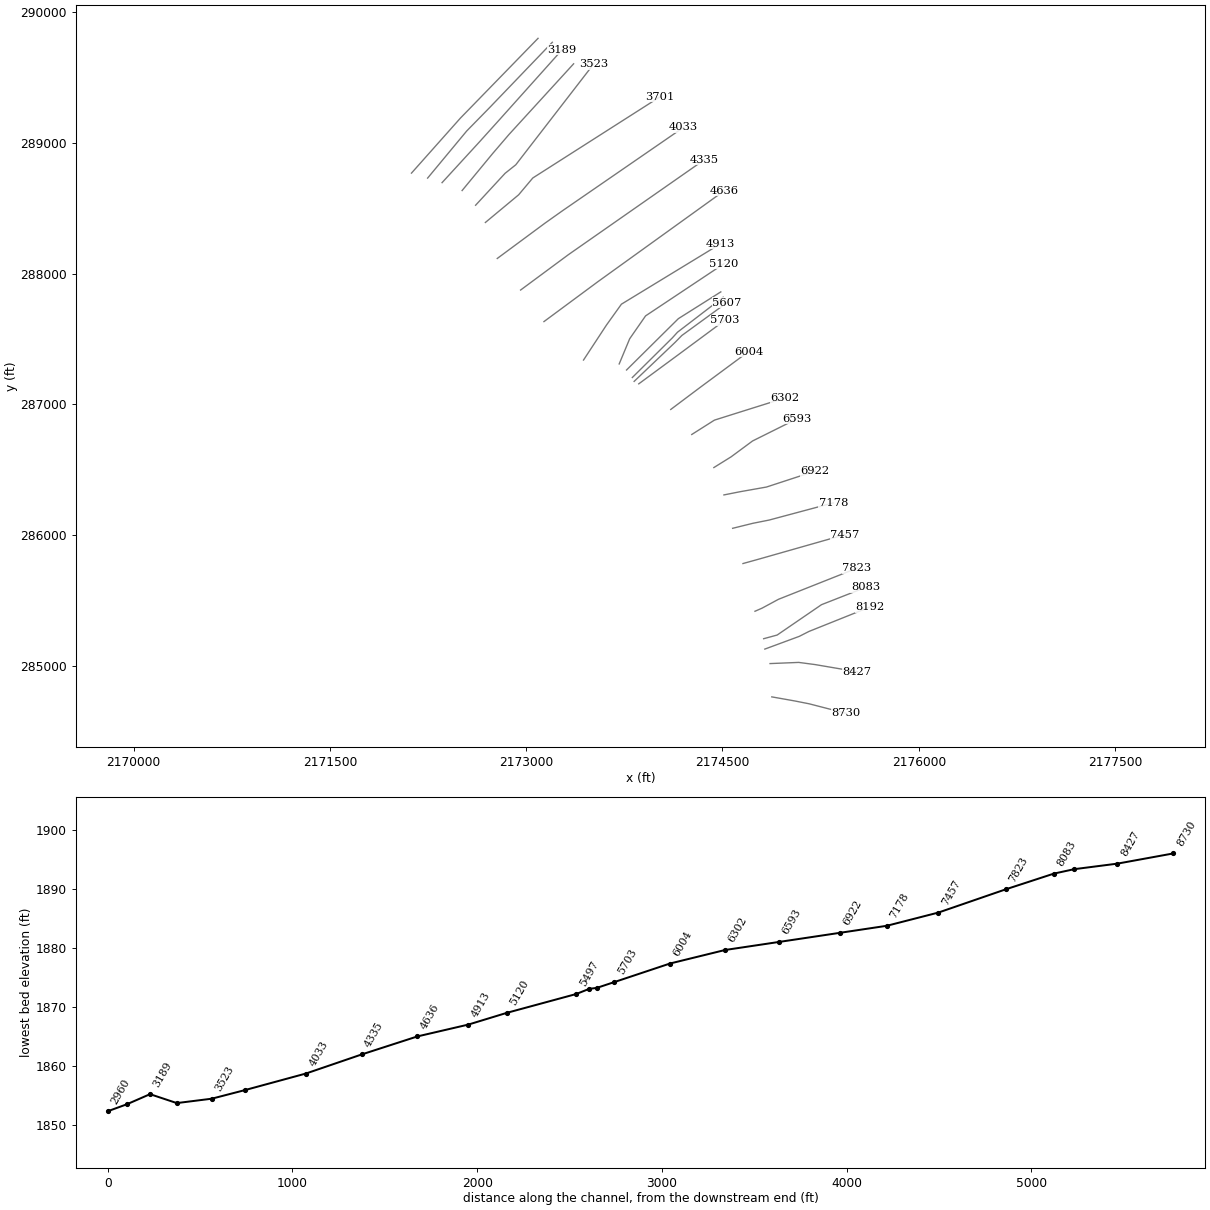
HEC-RAS study DRYCK1.prj: DRYCK1

--- DRYCK1.g01 (geometry) --- (continued)

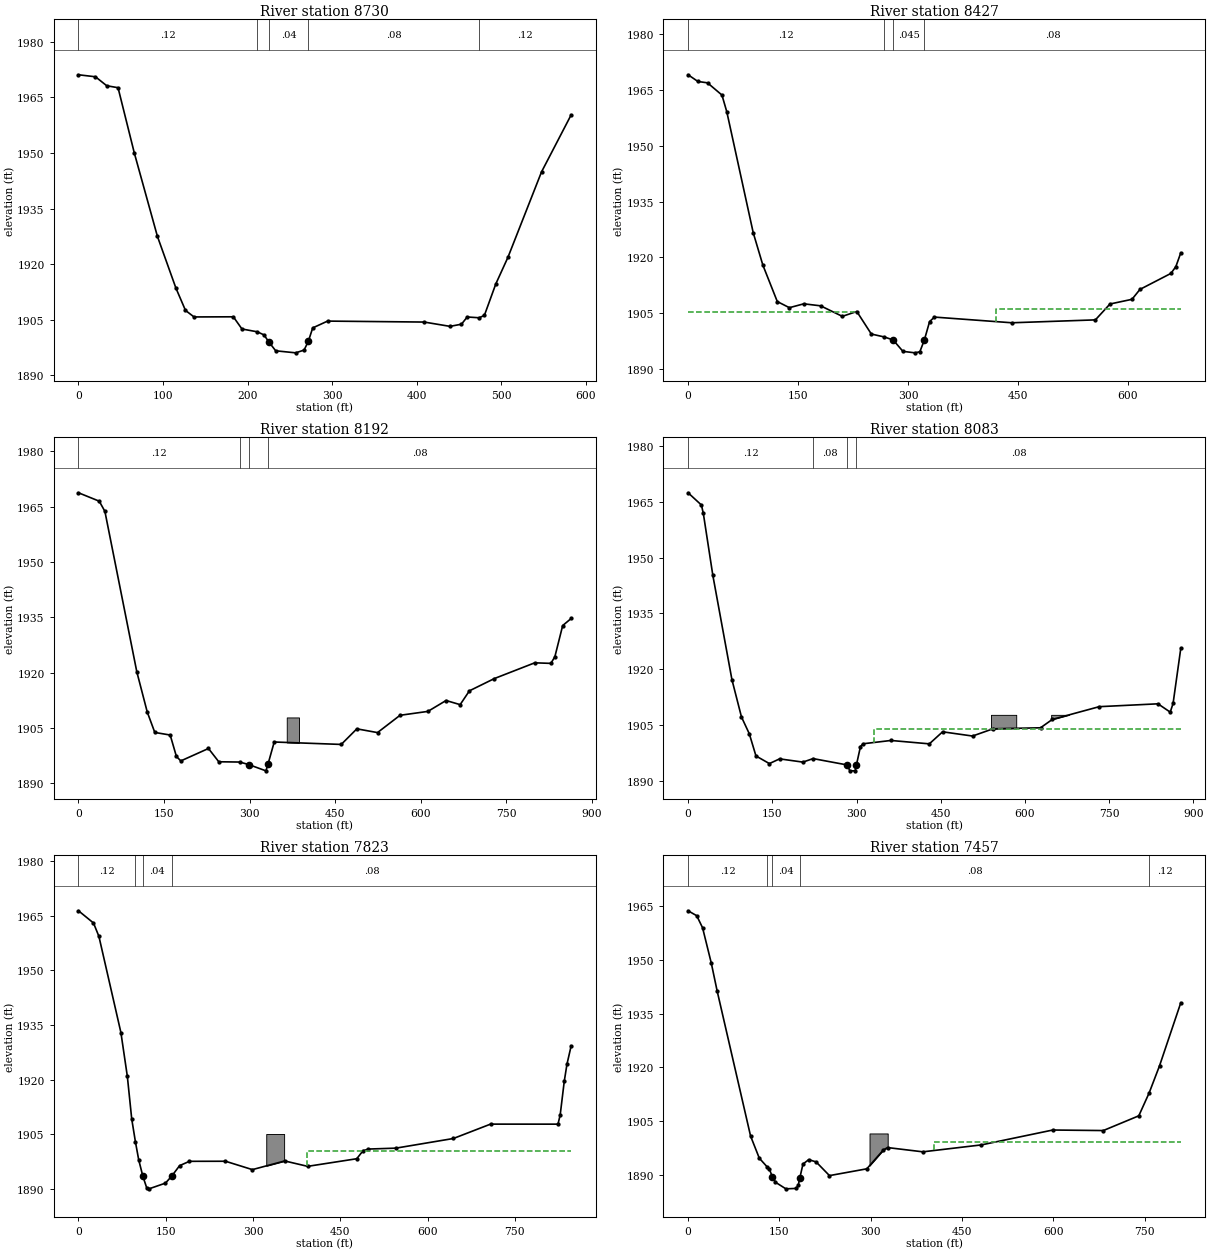
Type RM Length L Ch R = 1 ,8730    ,299.6,303.2,304.6
XS GIS Cut Line= 4
     2174877.017      284765.622     2175053.816      284734.187
     2175163.031      284712.533     2175445.983      284639.512
#Sta/Elev= 30
       0 1971.12    20.1 1970.58    33.4 1968.16    46.8 1967.63    66.1 1949.96
    93.4 1927.48   115.3 1913.51   126.6  1907.5   136.7 1905.74   183.2 1905.78
   193.4 1902.49  211.541901.727   219.5 1900.89     225 1899.06   233.3  1896.6
     257 1896.05   266.9  1896.8     272  1899.2   277.1 1902.78   294.7 1904.62
     409 1904.36   439.5  1903.2   453.1 1903.78   459.9 1905.73  473.931905.518
   480.2 1906.15   493.7 1914.64   508.1 1921.85   547.8 1944.89   582.9 1960.31
#Mann= 5 ,-1 , 0
       0     .12       0  211.54     .08       0     225     .04       0
     272     .08       0  473.93     .12       0
Bank Sta=225,272
XS Rating Curve= 0 ,0
Exp/Cntr=0.3,0.1

Type RM Length L Ch R = 1 ,8427    ,211,234.2,245.8
XS GIS Cut Line= 4
     2174863.776      285020.009     2175082.639      285028.948
     2175207.349      285012.457     2175530.243      284957.469
#Sta/Elev= 30
       0 1969.14    13.4 1967.34    26.5 1966.97    46.2 1963.68    52.8 1959.19
    88.9 1926.61     102 1917.93   121.7 1908.12   138.2 1906.47   157.9 1907.51
   180.8 1906.97   210.4 1904.14   230.2 1905.44     250 1899.38  267.891898.581
   279.8 1897.78   293.1 1894.72   309.6 1894.32   316.2 1894.61   322.4 1897.81
   329.5 1902.73   336.1 1903.94   441.7 1902.41   555.7 1903.19   575.6 1907.46
   605.6 1908.72  616.511911.391   658.8  1915.7   665.5 1917.53   672.2 1921.23
#Mann= 4 ,-1 , 0
       0     .12       0  267.89     .08       0   279.8    .045       0
   322.4     .08       0
#XS Ineff= 2 , 0
             231 1905.42   419.9         1906.13
Permanent Ineff=
       F       F
Bank Sta=279.8,322.4
XS Rating Curve= 0 ,0
Exp/Cntr=0.3,0.1

Type RM Length L Ch R = 1 ,8192    ,97.8,109.9,112.1
XS GIS Cut Line= 4
     2174823.831      285130.731       2175087.3      285228.118
     2175160.804      285265.487     2175625.405      285451.672
#Sta/Elev= 30
       0 1968.78    36.4  1966.5    46.3 1963.74   102.3 1920.21   120.6 1909.31
   133.8 1903.79   160.8 1903.09   171.7 1897.28   179.4 1896.07   227.9 1899.44
     246 1895.84  282.841895.765   298.6 1895.07   328.7 1893.38   332.2 1895.14
   343.2  1901.2   460.7 1900.54   488.1 1904.77   524.3 1903.75   563.8 1908.44
   612.7  1909.5   644.5 1912.45   669.2 1911.33   685.5 1915.08   729.3 1918.41
     800 1922.67   828.3 1922.52   835.3 1924.32     849 1932.77   863.9  1934.7
#Mann= 4 ,-1 , 0
       0     .12       0  282.84     .08       0   298.6     .04       0
   332.2     .08       0
#Block Obstruct= 2 ,-1
  365.18  386.58 1907.86  580.25  620.15 1907.86
Bank Sta=298.6,332.2
XS Rating Curve= 0 ,0
Exp/Cntr=0.3,0.1

Type RM Length L Ch R = 1 ,8083    ,234.9,259.7,222.6
XS GIS Cut Line= 4
     2174814.927      285210.026     2174918.077      285238.155
     2175256.821      285470.074     2175592.001      285601.567
#Sta/Elev= 30
       0 1967.43    23.7 1964.14    27.1 1961.92    44.1 1945.19    78.1 1917.15
    95.1 1907.11     109 1902.61   120.9 1896.63   144.8 1894.58     163 1895.85
   204.4 1894.98  222.67 1895.92   283.9  1894.2   287.9 1892.63   297.6 1892.63
   299.8 1894.22     307 1899.16   311.7 1899.91   361.3  1900.8   429.7 1899.89
   453.3 1903.13   506.6 1901.99   543.1 1903.94   627.7 1904.21   648.7 1906.46
   732.2 1909.89   836.9 1910.66   858.7 1908.42   863.8 1910.77   877.5 1925.57
#Mann= 4 ,-1 , 0
       0     .12       0  222.67     .08       0   283.9     .04       0
   299.8     .08       0
#XS Ineff= 2 , 0
                           330.5         1904.01
Permanent Ineff=
       F       F
#Block Obstruct= 2 ,-1
  539.42  584.41 1907.69  646.62  754.49 1907.69
Bank Sta=283.9,299.8
XS Rating Curve= 0 ,0
Exp/Cntr=0.3,0.1

Type RM Length L Ch R = 1 ,7823    ,361.9,365.4,336
XS GIS Cut Line= 4
     2174748.536      285419.844     2174802.297      285443.276
     2174928.256      285511.274     2175527.965      285749.079
#Sta/Elev= 30
       0 1966.37    25.8 1963.01    35.1 1959.34    72.9 1932.93      84 1920.85
    91.5 1909.18   97.861902.897   103.5 1897.96   110.6 1893.47   117.6 1890.09
   121.2 1889.98   149.5 1891.55   160.4  1893.5   173.8 1896.35   190.7 1897.54
   252.7 1897.56   298.9 1895.26   354.5 1897.64   393.9 1896.16   478.3 1898.25
   489.1 1900.44   498.5 1900.91   545.6 1901.16   644.4 1903.81   708.3 1907.76
   824.2 1907.75     828 1910.27     835 1919.52   839.7 1924.26   846.9 1929.28
#Mann= 4 ,-1 , 0
       0     .12       0   97.86     .08       0   110.6     .04       0
   160.4     .08       0
#XS Ineff= 2 , 0
                           393.5         1900.45
Permanent Ineff=
       F       F
#Block Obstruct= 1 ,-1
  322.74  353.47 1905.05
Bank Sta=110.6,160.4
XS Rating Curve= 0 ,0
Exp/Cntr=0.3,0.1

Type RM Length L Ch R = 1 ,7457    ,277.4,279.2,278.9
XS GIS Cut Line= 3
     2174656.765      285784.366     2174788.847      285821.138
     2175435.643      286005.184
#Sta/Elev= 30
       0  1963.8    14.2 1962.42    23.8 1959.04      38 1949.26    47.8 1941.33
   102.7 1900.79     117 1894.62  129.411892.273   133.4 1891.64   138.3 1889.46
   143.6 1887.88   160.7 1886.04   177.7 1886.16   181.1 1887.08   183.5 1889.03
   188.8 1892.98   198.2  1894.2   210.3 1893.58   232.3 1889.74   293.7 1891.64
     321 1896.94   327.8 1897.58   385.8 1896.39   482.1 1898.33   599.3 1902.49
   682.3 1902.34   740.6 1906.46  757.671912.881   774.7 1920.46   809.6 1938.07
#Mann= 5 ,-1 , 0
       0     .12       0  129.41     .08       0   138.3     .04       0
   183.5     .08       0  757.67     .12       0
#XS Ineff= 2 , 0
                           404.6         1899.02
Permanent Ineff=
       F       F
#Block Obstruct= 2 ,-1
  298.13  328.01 1901.53  587.63  628.65 1901.53
Bank Sta=138.3,183.5
XS Rating Curve= 0 ,0
Exp/Cntr=0.3,0.1

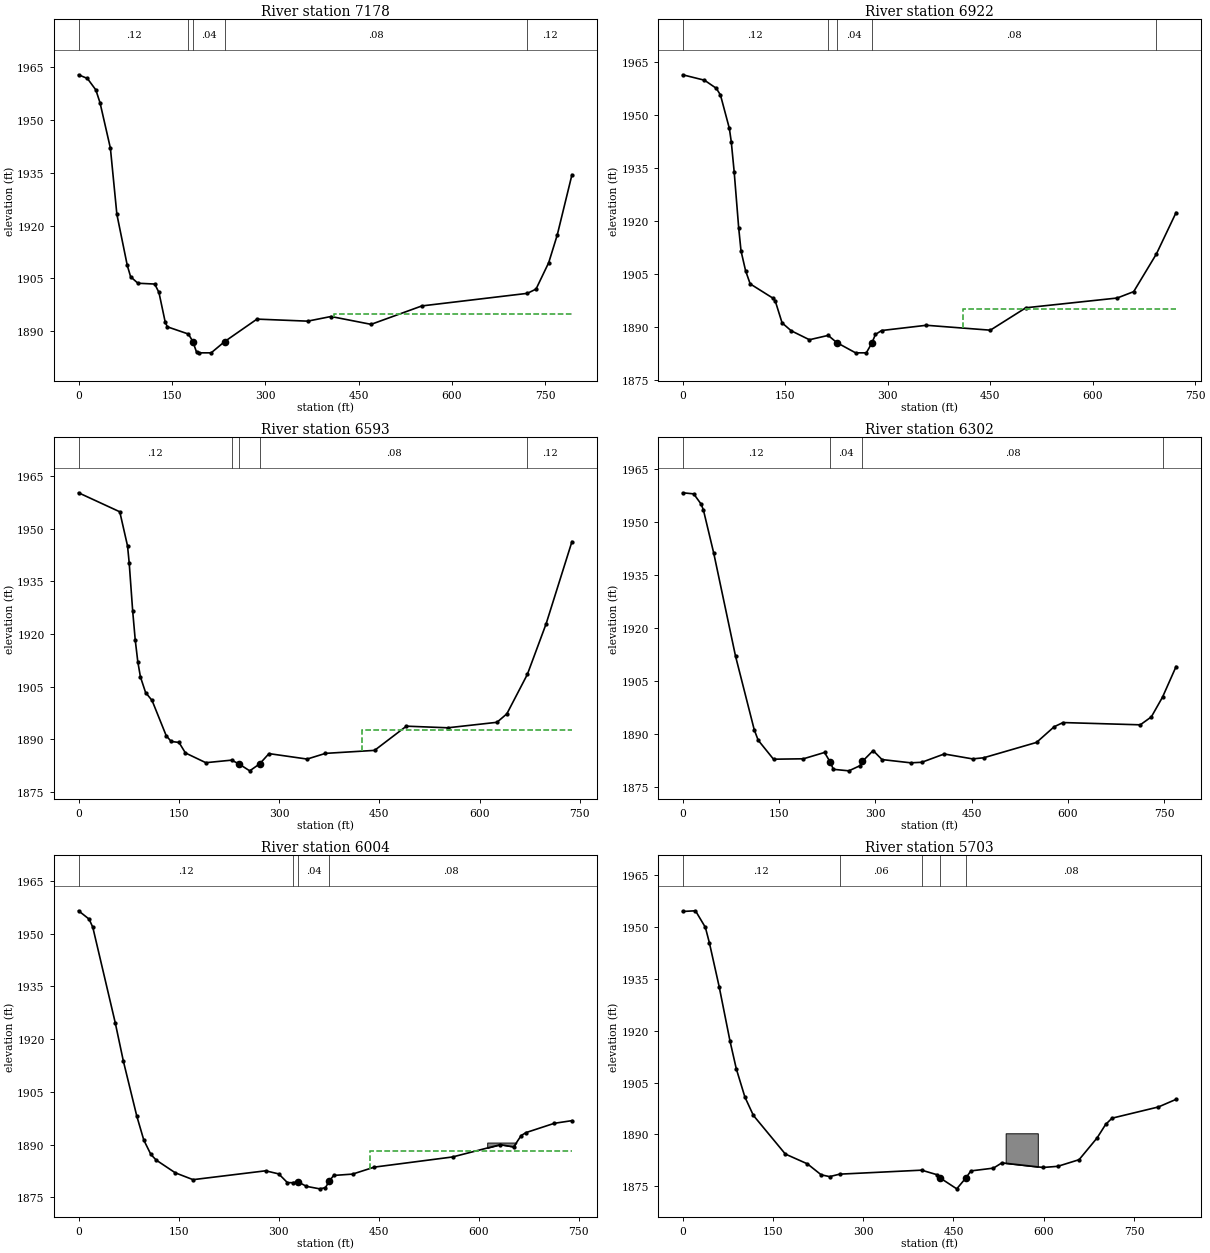
Type RM Length L Ch R = 1 ,7178    ,255.7,256,254.7
XS GIS Cut Line= 4
     2174577.881      286053.693     2174732.139      286091.845
     2174856.743      286116.683     2175346.207      286247.681
#Sta/Elev= 30
       0 1962.86    14.2 1961.82    27.8 1958.56    34.5 1954.93    51.2    1942
    61.6 1923.19    78.3 1908.67    83.7 1905.43    95.4 1903.59   122.4 1903.36
   129.2 1900.97   139.3 1892.51   142.7  1891.2  176.551889.145  184.27 1886.84
  184.27 1886.67   189.7 1883.96     193  1883.8   213.1  1883.8   234.9 1887.02
   286.7 1893.39   368.1 1892.81   405.6 1894.13     470  1891.9   551.6 1897.14
   721.11900.717     735 1901.93   755.4 1909.47     769 1917.26   792.7 1934.44
#Mann= 5 ,-1 , 0
       0     .12       0  176.55     .08       0  184.27     .04       0
   234.9     .08       0   721.1     .12       0
#XS Ineff= 2 , 0
                           410.3         1894.91
Permanent Ineff=
       F       F
Bank Sta=184.27,234.9
XS Rating Curve= 0 ,0
Exp/Cntr=0.3,0.1

Type RM Length L Ch R = 1 ,6922    ,302.7,328.8,347.9
XS GIS Cut Line= 4
      2174511.23      286308.749      2174632.76      286332.869
     2174836.336       286368.99     2175208.497      286490.736
#Sta/Elev= 30
       0 1961.39    31.9 1959.85    49.2 1957.56    55.3 1955.66    68.3 1946.22
    71.1 1942.46    75.4 1933.86      82 1917.99    85.4 1911.48    92.1 1905.85
    98.8 1902.14   132.2 1898.08   135.5  1897.3   145.5 1891.09   158.8 1888.86
   185.5 1886.31  212.981887.542   225.5 1885.51   253.1  1882.6   268.8  1882.6
   276.9 1885.37   282.1  1887.8   291.1 1888.92   356.7 1890.41   450.3 1889.02
   502.3 1895.37   635.9 1898.13   660.1 1899.94  693.381910.628   722.2 1922.36
#Mann= 5 ,-1 , 0
       0     .12       0  212.98     .08       0   225.5     .04       0
   276.9     .08       0  693.38     .12       0
#XS Ineff= 2 , 0
                           410.3         1894.91
Permanent Ineff=
       F       F
Bank Sta=225.5,276.9
XS Rating Curve= 0 ,0
Exp/Cntr=0.3,0.1

Type RM Length L Ch R = 1 ,6593    ,297.5,291.3,259.6
XS GIS Cut Line= 4
     2174434.338      286517.824     2174566.563      286600.092
     2174730.164      286721.054       2175069.3      286890.069
#Sta/Elev= 30
       0 1960.18    61.7 1954.77    73.3 1945.06    75.8 1940.23      81 1926.56
    84.9 1918.16    88.7 1912.07    92.6  1907.8   100.3 1903.35     110 1901.08
   131.2 1891.05   138.6 1889.42   150.3 1889.14   159.9 1886.15   190.4 1883.38
  228.941884.102   239.7 1883.06   256.1 1881.06     271 1883.05   284.9 1885.96
     342 1884.41   369.4 1886.03   442.8 1886.88   490.4 1893.77   552.4 1893.31
   625.9 1894.87   640.7 1897.28  671.35 1908.49   699.4 1922.87   738.1 1946.29
#Mann= 5 ,-1 , 0
       0     .12       0  228.94     .08       0   239.7     .04       0
     271     .08       0  671.35     .12       0
#XS Ineff= 2 , 0
                           424.6          1892.6
Permanent Ineff=
       F       F
Bank Sta=239.7,271
XS Rating Curve= 0 ,0
Exp/Cntr=0.3,0.1

Type RM Length L Ch R = 1 ,6302    ,277.2,298.2,314.9
XS GIS Cut Line= 4
     2174265.454      286770.532     2174438.741      286880.288
     2174628.383      286940.067     2174976.403      287049.333
#Sta/Elev= 30
       0 1958.37    17.2 1958.06    28.9 1955.12    32.4 1953.43    48.3 1941.36
    82.3 1912.18   111.5 1891.31   117.6 1888.37   141.5 1882.99   188.1 1883.11
     221  1884.9   229.6 1882.24   234.8 1880.13   258.9  1879.7   276.1 1881.15
     280 1882.38   296.7 1885.43   310.5 1882.89   355.2 1881.97   372.4 1882.12
   407.4 1884.47   451.5 1883.08   468.7 1883.39   551.2 1887.74   578.7 1892.18
   592.5 1893.36   712.8 1892.72     730 1894.96  747.421900.545   768.6 1909.22
#Mann= 4 ,-1 , 0
       0     .12       0   229.6     .04       0     280     .08       0
  747.42     .12       0
Bank Sta=229.6,280
XS Rating Curve= 0 ,0
Exp/Cntr=0.3,0.1

Type RM Length L Ch R = 1 ,6004    ,308.1,300.4,300.9
XS GIS Cut Line= 3
     2174104.805      286961.711     2174332.801      287132.811
     2174698.572      287403.434
#Sta/Elev= 30
       0 1956.51    15.9 1954.13    21.4 1951.82      55 1924.72    67.3  1913.7
    87.4  1898.1    97.9 1891.28   108.5  1887.2   116.5 1885.59   145.2 1881.96
   171.8 1880.02   280.6 1882.54   300.3 1881.66   313.3 1879.18  320.971879.158
   328.9 1879.44   341.8 1878.12   361.7 1877.41   370.4 1877.75   375.8 1879.54
   382.7 1881.22     411  1881.6   443.7 1883.59   561.1 1886.48   632.7 1889.98
   652.6 1889.34     664 1892.58   671.3 1893.42   713.6 1896.05   740.1 1896.81
#Mann= 4 ,-1 , 0
       0     .12       0  320.97     .08       0   328.9     .04       0
   375.8     .08       0
#XS Ineff= 2 , 0
                          437.17         1888.08
Permanent Ineff=
       F       F
#Block Obstruct= 1 ,-1
  612.99  662.32 1890.58
Bank Sta=328.9,375.8
XS Rating Curve= 0 ,0
Exp/Cntr=0.3,0.1

Type RM Length L Ch R = 1 ,5703    ,75.4,96.3,101
XS GIS Cut Line= 3
     2173860.537      287157.537     2174154.368      287373.979
     2174520.139      287644.601
#Sta/Elev= 30
       0 1954.48    21.3 1954.68    37.7 1949.89    44.3 1945.48    60.6 1932.77
    78.7 1916.96    89.1 1908.99   103.4 1900.82   117.5 1895.51   170.6 1884.34
   207.2 1881.51   230.1 1878.34   244.2 1877.81   260.81878.524  397.051879.679
   423.3 1878.33     427 1877.52   455.4 1874.28   471.1 1877.53   478.8 1879.46
   516.4 1880.27   530.4 1881.79   598.8 1880.46   623.3 1880.79   658.7 1882.71
   688.6    1889   702.8  1892.9   713.4 1894.71   790.6 1897.96   819.9 1900.16
#Mann= 5 ,-1 , 0
       0     .12       0   260.8     .06       0  397.05     .12       0
     427     .04       0   471.1     .08       0
#Block Obstruct= 2 ,-1
  536.67  590.07 1890.34  722.09  731.49 1890.34
Bank Sta=427,471.1
XS Rating Curve= 0 ,0
Exp/Cntr=0.5,0.3

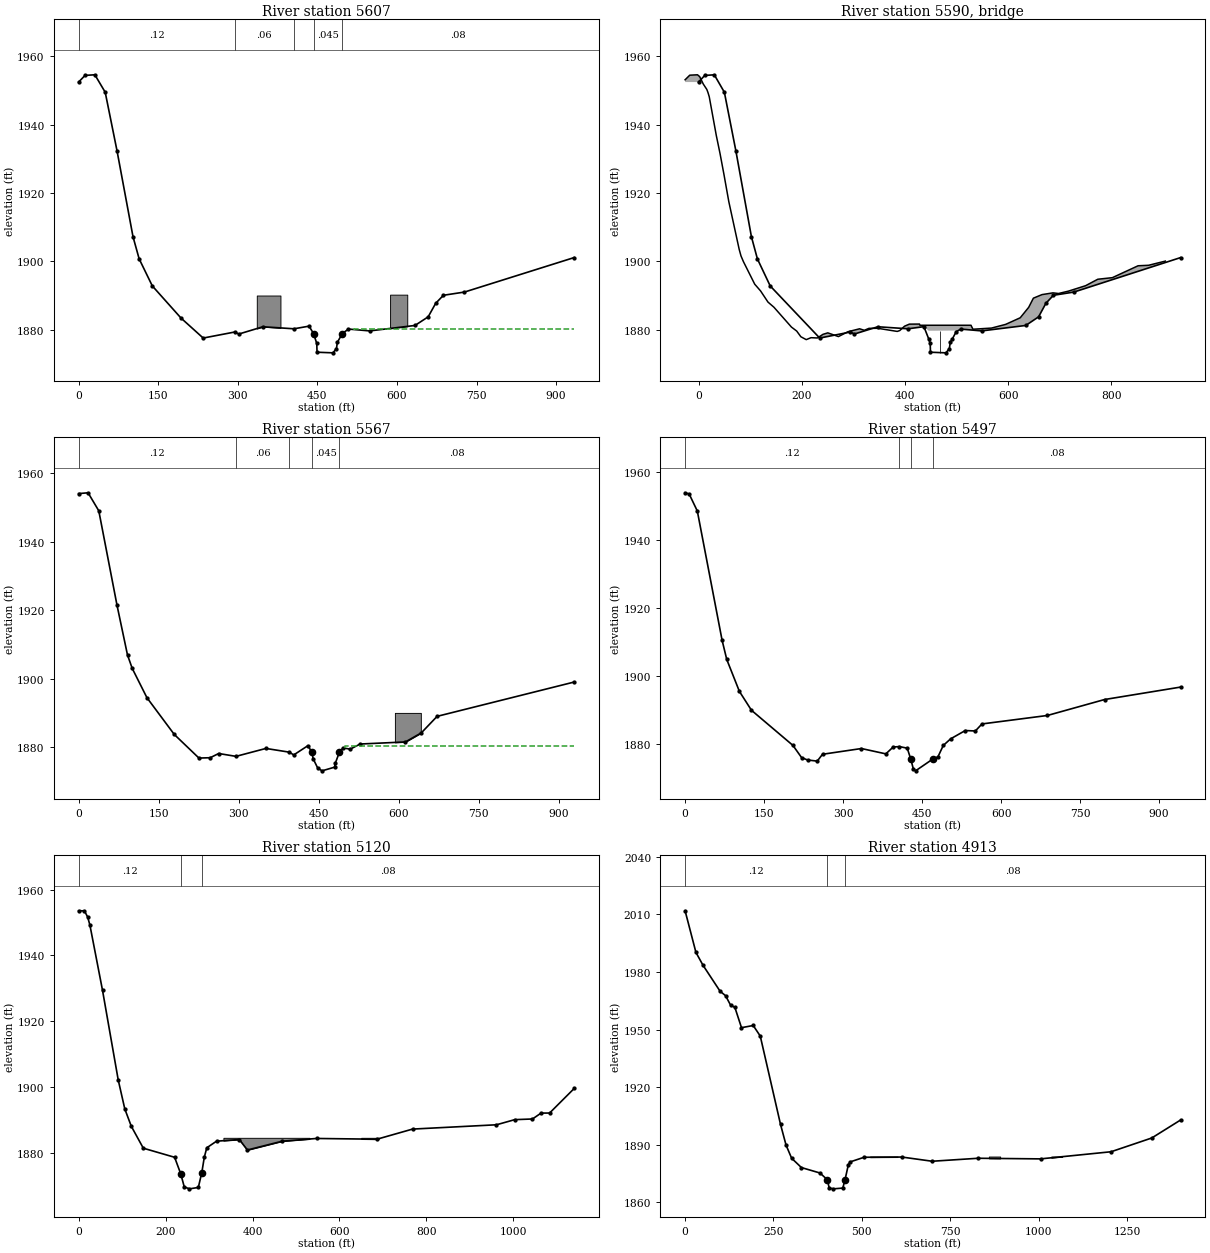
Type RM Length L Ch R = 1 ,5607    ,36.9,40,41.2
BEGIN DESCRIPTION:
Merged DS Survey DRC042BU
END DESCRIPTION:
XS GIS Cut Line= 4
     2173825.165      287176.185     2174138.179        287474.6
     2174189.573      287526.964     2174535.752      287779.083
#Sta/Elev= 30
       0 1952.41    12.1 1954.35    30.6 1954.53    50.1 1949.43    72.4 1932.29
   102.5 1907.21   114.1 1900.73   138.9 1892.83     193 1883.44   234.8  1877.6
  293.861879.352   302.1 1878.78   347.4  1880.9     4061880.307   434.4 1881.08
   442.9 1878.88   448.9 1876.01   449.4 1873.46   479.4 1873.28     486 1874.52
   487.7 1876.35     497  1878.9   508.6 1880.23   548.6 1879.69     634 1881.28
   658.9  1883.8     673 1887.74   687.6  1890.1   727.3 1891.04   934.1 1901.12
#Mann= 5 ,-1 , 0
       0     .12       0  293.86     .06       0     406     .08       0
   442.9    .045       0     497     .08       0
#XS Ineff= 2 , 0
          425.52 1880.37  519.51         1880.28
Permanent Ineff=
       F       F
#Block Obstruct= 4 ,-1
  335.81  380.42 1890.03  587.09  619.471890.285  685.21  705.47 1890.03
  724.42  771.42 1890.03
Bank Sta=442.9,497
XS Rating Curve= 0 ,0
Exp/Cntr=0.5,0.3

Type RM Length L Ch R = 3 ,5590    ,,,
BEGIN DESCRIPTION:
Merged US Survey DRC040RP
Unnamed Rd
END DESCRIPTION:
Bridge Culvert--1,0,-1,-1, 0
Deck Dist Width WeirC Skew NumUp NumDn MinLoCord MaxHiCord MaxSubmerge Is_Ogee
14,10,2.6,0, 60, 60, , , 0.98, 0, 0,0,,
     -26     -17      -2     2.2     9.2    16.1    18.4    20.8    34.4    41.7
    49.2    58.7    78.8    82.3    87.1   108.9   120.2   134.6   146.1   180.1
   190.2   198.3   208.7     218   230.2   241.2   250.5   271.1   289.4   312.1
   321.2   330.3   347.3     385   389.9   399.2   408.5   428.1   429.2  433.06
  433.16  506.17  506.27   527.9   531.7   567.7   595.1   623.3   639.7   648.8
   665.5   686.7   697.5   716.4   749.9   773.6   801.8   851.7     872   904.5
 1953.08 1954.42 1954.54 1954.01 1951.84 1950.25 1949.32 1948.12 1936.84 1931.51
 1925.48 1917.46 1903.52  1901.6  1899.9 1893.34 1891.38 1888.11 1886.61  1880.8
 1879.65 1877.98 1877.14 1877.71 1877.62 1878.69 1879.12 1878.03 1879.45 1880.31
 1879.87 1880.44 1880.45 1879.54 1879.79 1881.07 1881.67 1881.69 1881.32 1881.34
 1881.34 1881.34 1881.34 1881.34 1880.18 1880.52  1881.6 1883.53 1886.58 1889.26
  1890.3 1890.81 1890.62  1891.3  1892.9 1894.79 1895.25 1898.73 1898.87 1900.09
                                                                                
                                                                                
                                                                                
                                                                                
 1879.72  1879.8
                                                                                
     -26     -17      -2     2.2     9.2    16.1    18.4    20.8    34.4    41.7
    49.2    58.7    78.8    82.3    87.1   108.9   120.2   134.6   146.1   180.1
   190.2   198.3   208.7     218   230.2   241.2   250.5   271.1   289.4   312.1
   321.2   330.3   347.3     385   389.9   399.2   408.5   428.1   429.2  433.06
  433.16     500  506.27   527.9   531.7   567.7   595.1   623.3   639.7   648.8
   665.5   686.7   697.5   716.4   749.9   773.6   801.8   851.7     872   904.5
 1953.08 1954.42 1954.54 1954.01 1951.84 1950.25 1949.32 1948.12 1936.84 1931.51
 1925.48 1917.46 1903.52  1901.6  1899.9 1893.34 1891.38 1888.11 1886.61  1880.8
 1879.65 1877.98 1877.14 1877.71 1877.62 1878.69 1879.12 1878.03 1879.45 1880.31
 1879.87 1880.44 1880.45 1879.54 1879.79 1881.07 1881.67 1881.69 1881.32 1881.34
 1881.34 1881.34 1881.34 1881.34 1880.18 1880.52  1881.6 1883.53 1886.58 1889.26
  1890.3 1890.81 1890.62  1891.3  1892.9 1894.79 1895.25 1898.73 1898.87 1900.09
                                                                                
                                                                                
                                                                                
                                                                                
 1879.72  1879.8
                                                                                
Pier Skew, UpSta & Num, DnSta & Num=  ,467.5, 2 ,461.2, 2 , 0 , 0 , 0 ,,
      .8      .8
    1870    1880
      .8      .8
    1870    1880
BR Coef=-1 , 1 , 0 ,, 0 ,,,0.8,0,1.2,0,
WSPro=,,,, 1 ,,,, 0 ,,,, 0 ,,,,-1 ,-1 ,-1 , 0 , 0 , 0 , 0 , 0
BR U #Sta/Elev= 30
       0 1952.41    12.1 1954.35    30.6 1954.53    50.1 1949.43    72.4 1932.29
   102.5 1907.21   114.1 1900.73   138.9 1892.83   234.8  1877.6  293.861879.352
   302.1 1878.78   347.4  1880.9     4061880.307   436.7 1880.93     446 1877.35
   448.9 1876.01   449.4 1873.46   479.4 1873.28     486 1874.52   487.7 1876.35
  491.65 1877.31   499.3 1879.47   508.2 1880.22   548.6 1879.69     634 1881.28
   658.9  1883.8     673 1887.74   687.6  1890.1   727.3 1891.04   934.1 1901.12
BR U #Mann= 5
       0     .12  293.86     .06     406     .08     446     .04  491.65     .08
BR D #Sta/Elev= 30
       0 1954.08    17.7 1954.32    37.8 1949.05      72 1921.43    91.6 1906.95
   100.4 1903.06     128 1894.49   179.3 1883.75   225.5 1876.86   246.6 1876.96
   262.5 1878.19  294.921877.357     351 1879.67   395.21878.576   403.1 1877.77
     431 1880.49   435.4 1879.36   439.8 1876.58     448 1873.98   456.2 1873.13
   479.9 1874.21   484.2 1876.54   491.5 1879.18   499.4 1880.04   508.1 1879.44
   527.7 1880.96   616.6 1881.81   642.4 1884.23   671.9 1889.04   928.8 1899.06
BR D #Mann= 5
       0     .12  294.92     .12   395.2     .08   439.8     .04   484.2     .08
BC Design=,, 0 ,, 0 ,,0,,,,
BC HTab HWMax=0
BC HTab TWMax=0
BC HTab MaxFlow=0
BC Use User HTab Curves=0
BC User HTab FreeFlow(D)= 0

Type RM Length L Ch R = 1 ,5567    ,73.2,70.7,70.3
BEGIN DESCRIPTION:
Merged US Survey DRC038BD
END DESCRIPTION:
XS GIS Cut Line= 4
     2173811.393      287205.996     2174116.846      287508.539
     2174156.603      287552.175     2174505.692       287819.81
#Sta/Elev= 30
       0 1954.08    17.7 1954.32    37.8 1949.05      72 1921.43    91.6 1906.95
   100.4 1903.06     128 1894.49   179.3 1883.75   225.5 1876.86   246.6 1876.96
   262.5 1878.19  294.921877.357     351 1879.67   395.21878.576   403.1 1877.77
   429.9 1880.49   436.8 1878.63   439.8 1876.58     448 1873.98   456.2 1873.13
   479.9 1874.21     481 1875.32   488.7 1878.53   495.6 1879.83     509 1879.46
   527.7 1880.96   612.6 1881.57   642.4 1884.23   671.9 1889.04   928.8 1899.06
#Mann= 5 ,-1 , 0
       0     .12       0  294.92     .06       0   395.2     .08       0
   436.8    .045       0   488.7     .08       0
#XS Ineff= 2 , 0
          428.83 1880.36   498.9         1880.36
Permanent Ineff=
       F       F
#Block Obstruct= 1 ,-1
  592.78  641.39 1890.05
Bank Sta=436.8,488.7
XS Rating Curve= 0 ,0
Exp/Cntr=0.5,0.3

Type RM Length L Ch R = 1 ,5497    ,159.9,376.2,360.1
XS GIS Cut Line= 4
     2173767.133      287263.353     2174037.776      287531.548
     2174163.321      287655.783     2174487.486      287860.182
#Sta/Elev= 30
       0 1954.01     7.7 1953.66    23.2 1948.65    70.3  1910.6    79.1    1905
   103.1 1895.61     126 1890.06   204.8 1879.72   221.1 1876.16   232.5 1875.44
   250.9 1875.11   260.9 1877.12   334.8 1878.81   381.2 1877.24   395.1 1879.26
  406.97 1879.38   421.8 1878.91   428.7  1875.6   433.3 1872.84   437.6 1872.25
   470.7 1875.76     480 1876.35   490.2 1879.71   504.1 1881.65     532  1884.1
   551.1 1883.97   563.7 1886.04   687.9 1888.53   796.5 1893.22   940.9 1896.88
#Mann= 4 ,-1 , 0
       0     .12       0  406.97     .08       0   428.7     .04       0
   470.7     .08       0
#Block Obstruct= 1 ,-1
  850.92  898.92 1889.81
Bank Sta=428.7,470.7
XS Rating Curve= 0 ,0
Exp/Cntr=0.5,0.3

Type RM Length L Ch R = 1 ,5120    ,206.9,207.5,209.7
XS GIS Cut Line= 4
     2173710.998      287309.614     2173791.218      287502.231
     2173912.536       287676.78     2174510.787      288074.963
#Sta/Elev= 30
       0 1953.57    13.3 1953.55    20.8 1951.66    25.9 1949.24      55 1929.35
    91.1 1902.14   106.2 1893.34   121.2 1888.06   148.8 1881.41   220.8 1878.65
   234.9 1873.61     243 1869.64   254.9 1869.06   275.3 1869.48   283.3 1873.97
   289.1 1878.68   294.8 1881.54   317.2 1883.54   369.6 1884.05   388.1 1880.86
   468.3 1883.54   547.4 1884.37   686.2 1884.14   768.1 1887.22   961.2 1888.53
  1003.2 1890.09    1044 1890.29  1063.7 1892.08  1083.4  1892.1  1139.9 1899.56
#Mann= 3 ,-1 , 0
       0     .12       0   234.9    .045       0   283.3     .08       0
#Block Obstruct= 4 ,-1
  333.06  531.07 1884.57  650.01  691.47 1884.57  815.11  863.72 1884.57
  939.39  965.97 1884.57
Bank Sta=234.9,283.3
XS Rating Curve= 0 ,0
Exp/Cntr=0.3,0.1

Type RM Length L Ch R = 1 ,4913    ,291,276.5,272.4
XS GIS Cut Line= 4
     2173438.376       287339.41      2173613.24      287605.985
     2173727.963      287766.275     2174484.221      288227.097
#Sta/Elev= 30
       0 2011.79    30.6 1990.15    50.5 1983.48    98.9 1969.93   114.5 1967.59
   128.6 1962.69   140.8  1961.5   159.5 1950.95   192.7 1952.09   212.6 1946.57
   269.9  1900.6   285.6  1889.8   301.3 1883.01     329 1878.15   381.5 1875.32
  402.37 1871.81   407.6 1867.47   419.6 1867.08     446 1867.47  452.41 1871.89
   461.7  1879.6   466.4 1881.07   506.2 1883.51     613 1883.63   698.8 1881.44
   828.5 1882.99  1005.2 1882.67  1204.7 1886.38  1319.9 1893.55  1401.5 1902.92
#Mann= 3 ,-1 , 0
       0     .12       0  402.37     .04       0  452.41     .08       0
#Block Obstruct= 3 ,-1
  523.26  600.63  1883.9  859.13  891.01  1883.9 1035.66  1066.7  1883.9
Bank Sta=402.37,452.41
XS Rating Curve= 0 ,0
Exp/Cntr=0.3,0.1

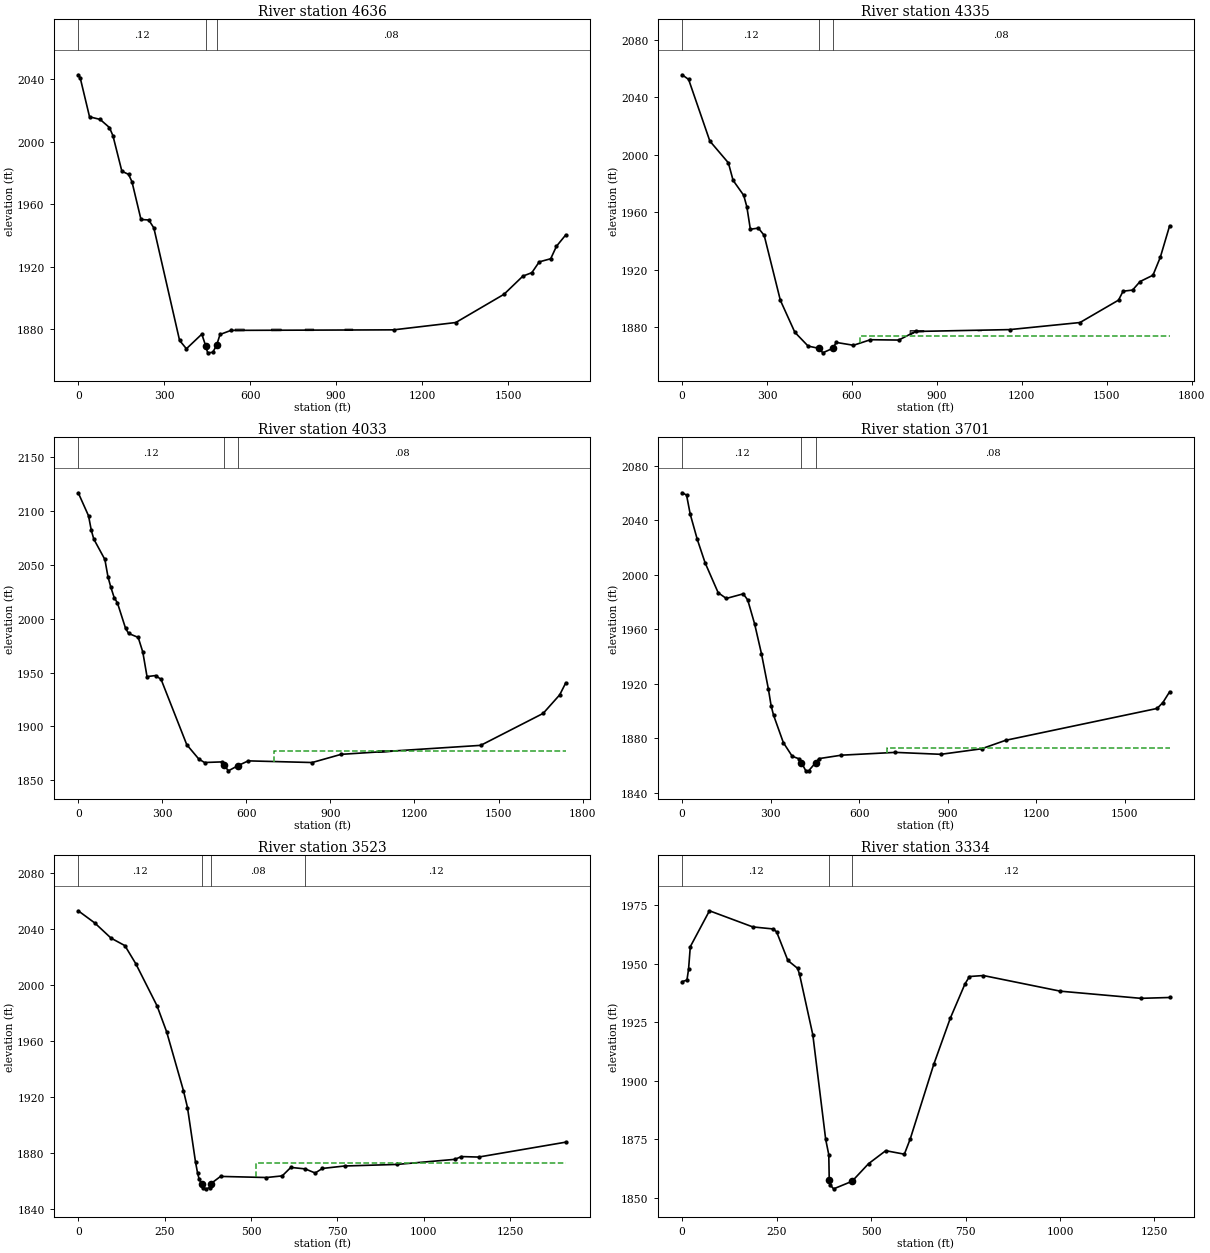
Type RM Length L Ch R = 1 ,4636    ,301.9,301.5,303.8
XS GIS Cut Line= 4
     2173136.095      287633.167     2173501.867       287903.79
     2173547.588      287937.654     2174513.015       288632.58
#Sta/Elev= 30
       0 2042.73     6.8 2040.83    39.5 2015.85    76.2 2014.23   108.8 2009.04
   121.1 2003.82   152.3 1981.11   175.7  1979.1   187.5 1974.39     219 1950.27
   246.1 1949.95   263.9 1944.87   353.7    1873   377.5 1867.68   431.3 1877.01
     445 1869.42   451.7 1865.07   469.6  1865.4     483 1869.97   494.8  1876.8
   533.1 1879.42  1100.6 1879.76  1317.5 1884.44  1485.9 1902.49  1551.8  1914.1
    1583 1916.29  1608.8 1923.19  1648.8 1925.19    1669 1933.19  1701.4 1940.44
#Mann= 3 ,-1 , 0
       0     .12       0     445     .04       0     483     .08       0
#Block Obstruct= 5 ,-1
  545.92  577.76 1880.53  672.67  706.71 1880.53  790.35  819.93 1880.53
  928.86  956.41 1880.53 1612.71 1640.44 1880.53
Bank Sta=445,483
XS Rating Curve= 0 ,0
Exp/Cntr=0.3,0.1

Type RM Length L Ch R = 1 ,4335    ,300.2,302,307.1
XS GIS Cut Line= 3
     2172957.663      287874.335     2173323.435      288144.957
       2174362.5      288870.464
#Sta/Elev= 30
       0 2055.76      23 2052.53      98 2009.58   163.5 1994.39   180.1 1982.22
   217.7 1971.74   228.8 1963.71   241.1 1948.13   269.6 1948.93     290 1943.85
   347.1 1898.62   398.3 1876.34   445.2 1866.72   485.2 1865.07   496.7 1862.02
   533.3 1865.25   544.1 1869.29   605.4 1867.29   665.4 1871.16   765.4 1870.92
   824.5 1876.91  1157.5 1878.21  1405.6 1883.14  1541.7 1898.75  1557.7 1904.96
  1591.2 1905.75  1617.7  1911.7  1663.3  1916.1  1689.3 1928.64  1722.2 1950.56
#Mann= 3 ,-1 , 0
       0     .12       0   485.2     .04       0   533.3     .08       0
#XS Ineff= 2 , 0
                           628.1          1874.1
Permanent Ineff=
       F       F
#Block Obstruct= 11 ,-1
  803.76   852.2 1877.82 1042.66  1070.1 1877.82 1082.91 1110.48 1877.82
  1166.7 1194.48 1877.82 1221.57 1241.97 1877.82 1251.07 1297.53 1877.82
 1304.15 1339.51 1877.82  1370.2 1396.99 1877.82 1485.34 1522.67 1877.82
 1553.66 1579.09 1877.82 1614.78 1653.47 1877.82
Bank Sta=485.2,533.3
XS Rating Curve= 0 ,0
Exp/Cntr=0.3,0.1

Type RM Length L Ch R = 1 ,4033    ,311.8,332,346.5
XS GIS Cut Line= 4
     2172779.231      288115.503     2173145.002      288386.125
     2173279.786      288481.662     2174201.959      289116.853
#Sta/Elev= 30
       0 2116.98    36.8 2095.58    46.7 2082.06    55.5 2074.01    95.1 2055.03
   106.1 2039.03   116.1 2029.49   128.3 2019.66     140 2014.69   169.1 1990.96
   179.9 1986.36     214 1982.69   230.4 1969.15   245.5 1946.31     276 1947.27
   295.7 1943.72   387.4 1883.04   430.3 1869.75   450.7 1866.53   513.1  1867.1
   521.6 1863.82   535.9 1858.79   569.6 1863.55   606.8 1868.05   834.8 1866.51
   938.4 1874.11  1436.4 1882.45  1659.3 1912.14  1718.3 1929.34    1740 1940.52
#Mann= 3 ,-1 , 0
       0     .12       0   521.6     .04       0   569.6     .08       0
#XS Ineff= 2 , 0
                             700         1877.45
Permanent Ineff=
       F       F
#Block Obstruct= 3 ,-1
 1068.18 1121.66 1877.98 1163.36 1210.59 1877.98 1226.23 1253.81 1877.98
Bank Sta=521.6,569.6
XS Rating Curve= 0 ,0
Exp/Cntr=0.3,0.1

Type RM Length L Ch R = 1 ,3701    ,182.8,177.8,167.7
XS GIS Cut Line= 4
     2172688.455      288390.602     2172942.535      288601.844
     2173050.749      288730.492     2174023.826      289351.489
#Sta/Elev= 30
       0 2060.21    15.1 2058.55    27.6 2044.45    51.5 2025.95      78 2008.77
   122.3  1986.8   149.8 1982.59   207.2 1985.97   222.5 1981.49   245.8 1963.96
   269.1 1941.98   292.4 1916.25   301.7 1903.93   309.9 1896.96   343.3 1876.69
   373.3 1866.68   394.7 1864.94  404.66 1862.02   419.2 1856.08  428.92 1855.97
   453.1 1862.05   464.7 1864.97   540.1 1867.47     723 1869.53   877.4 1868.11
  1015.2 1872.16  1096.7 1878.38  1610.4  1901.8  1629.9  1906.1  1652.9 1914.05
#Mann= 3 , 0 , 0
       0     .12       0  404.66    .045       0   453.1     .08       0
#XS Ineff= 2 , 0
                          693.68         1872.47
Permanent Ineff=
       F       F
#Block Obstruct= 2 ,-1
    1413 1464.94 1874.35  1532.8 1542.45 1874.35
Bank Sta=404.66,453.1
XS Rating Curve= 0 ,0
Exp/Cntr=0.3,0.1

Type RM Length L Ch R = 1 ,3523    ,185.7,189,196
XS GIS Cut Line= 4
     2172613.736      288522.236     2172839.452      288766.504
     2172920.875      288831.436     2173516.337      289601.994
#Sta/Elev= 30
       0 2052.82    47.8 2044.14      95 2033.31     135 2027.97   166.4 2015.12
   227.9  1985.1   255.7 1966.57   304.5 1924.49   316.1 1912.51   339.3 1873.69
   345.5 1865.55   349.7  1861.6  356.91 1858.17   362.3 1855.43   370.8 1854.53
   379.8 1855.43  383.01 1858.08   411.7 1863.39   544.6  1862.6   590.2 1863.77
   615.1 1869.81   656.51868.756   685.6 1865.82   706.3 1869.07   770.8 1870.82
   921.5 1871.93  1089.9 1875.57  1108.5 1877.54  1158.3 1877.19  1410.6 1887.82
#Mann= 4 ,-1 , 0
       0     .12       0  356.91     .04       0  383.01     .08       0
   656.5     .12       0
#XS Ineff= 2 , 0
                             515         1873.01
Permanent Ineff=
       F       F
Bank Sta=356.91,383.01
XS Rating Curve= 0 ,0
Exp/Cntr=0.5,0.3

Type RM Length L Ch R = 1 ,3334    ,142.6,144.8,135.5
BEGIN DESCRIPTION:
Merged DS Survey DRC032BU
END DESCRIPTION:
XS GIS Cut Line= 4
      2172510.67      288634.579     2172744.631      288918.012
     2172868.311      289062.306     2173362.713      289602.984
#Sta/Elev= 30
       0  1942.4    12.8 1943.04    17.1 1947.67    21.7 1957.34    72.4 1972.69
   187.1 1965.79   240.8 1964.92   250.1 1963.69   279.9 1951.45   305.6 1948.08
   310.7 1945.58     346  1919.6     380 1874.91   388.2 1868.37   389.4 1857.45
   390.8 1855.62   401.1 1853.79   449.8 1857.02   493.3 1864.53   538.9  1870.1
   588.2 1868.61   603.9 1875.21   665.9 1906.98   709.7 1926.73   748.6 1941.41
   760.5 1944.58   797.2    1945    1001 1938.31    1214 1935.25  1290.2 1935.61
#Mann= 3 ,-1 , 0
       0     .12       0   389.4     .04       0   449.8     .12       0
Bank Sta=389.4,449.8
XS Rating Curve= 0 ,0
Exp/Cntr=0.5,0.3

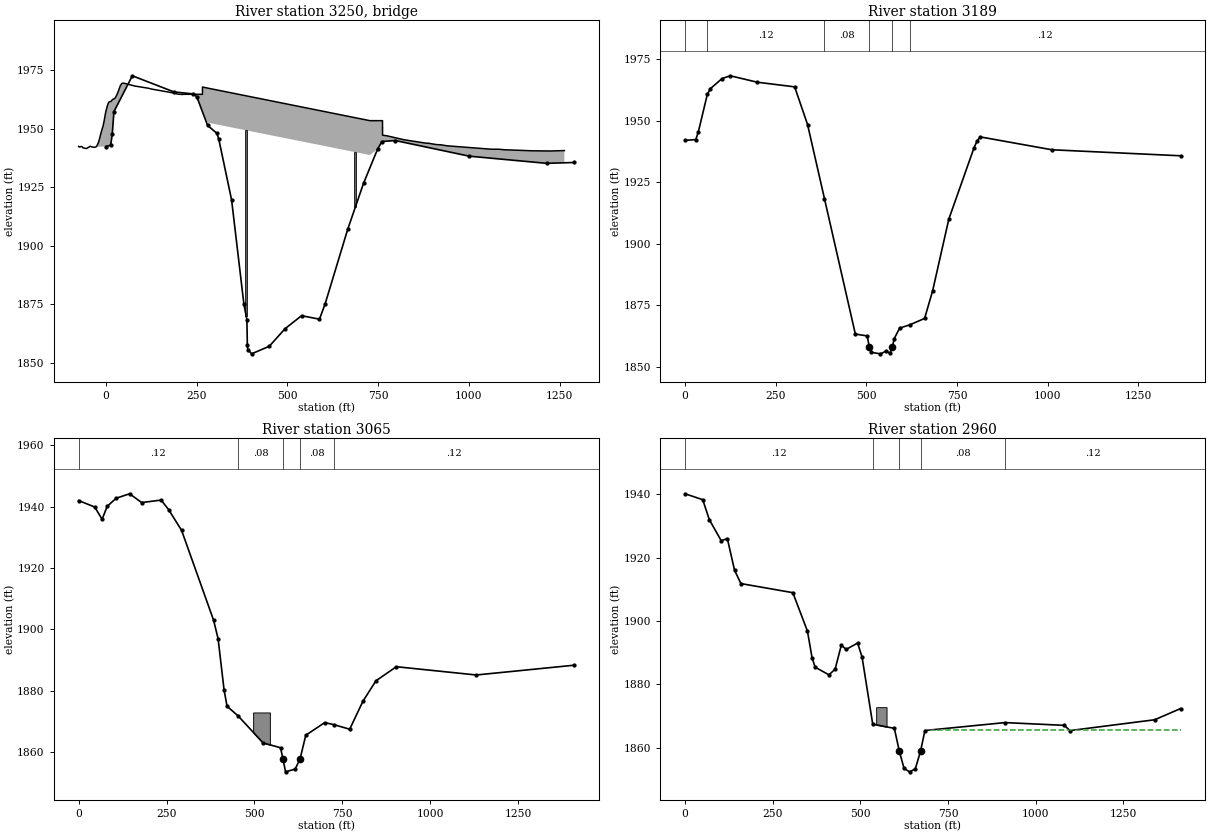
Type RM Length L Ch R = 3 ,3250    ,,,
BEGIN DESCRIPTION:
Merged DS Survey DRC030RP - Interstate 64
END DESCRIPTION:
Bridge Culvert--1,0,-1,-1, 0
Deck Dist Width WeirC Skew NumUp NumDn MinLoCord MaxHiCord MaxSubmerge Is_Ogee
24,100,2.6,0, 60, 60, , , 0.98, 0, 0,0,,
   -75.6     -74   -67.9   -65.9   -63.3     -54   -43.5   -37.7     -33   -28.4
   -26.1   -21.4   -19.1   -12.1    -8.7    -7.4    -5.1    -2.8     -.5     4.4
     6.5     8.7      14    17.4    22.8    26.1    30.5    34.8    39.2    43.7
      46    50.7    78.9   115.8   127.4   185.6   199.5   208.9  210.18  210.28
  265.71  265.71  727.12  761.97  761.97  762.07   762.1   775.1   820.2   880.6
   887.6   910.8   922.6   940.2  1061.8  1084.1  1096.6    1171  1224.4  1263.2
 1942.51 1942.23 1942.45  1942.3 1941.87 1941.57 1942.56  1942.2 1942.11 1942.23
 1942.46 1944.03 1945.14 1949.29 1950.96 1951.79 1953.55 1955.61 1957.49  1960.3
 1961.05 1961.58 1961.75  1962.5  1962.9 1963.42 1964.82  1966.5 1968.43 1969.45
 1969.54 1969.47 1968.31 1967.39 1966.95 1965.35 1964.79 1964.74 1964.63 1964.77
 1964.77 1967.87  1953.5  1953.5  1950.4  1950.4  1947.3 1946.99 1945.37  1943.9
 1943.86 1943.27 1943.18 1942.74 1941.29 1941.27 1941.07 1940.63 1940.53 1940.71
                                                                                
                                                                                
                                                                                
                                                                                
          1953.1  1938.8  1938.8
                                                                                
     -14   -12.4    -6.3    -4.3    -1.7     7.6    18.1    23.9    28.6    33.2
    35.5    40.2    42.5    49.5    52.9    54.2    56.5    58.8    61.1      66
    68.1    70.3    75.6      79    84.4    87.7    92.1    96.4   100.8   105.3
   107.6   112.3   140.5   177.4     189   247.2   261.1   270.5  271.78  271.88
  327.31  327.31  788.72  823.57  823.57  823.67   823.7   836.7   881.8   942.2
   949.2   972.4   984.2  1001.8  1123.4  1145.7  1158.2  1232.6    1286  1324.8
 1942.51 1942.23 1942.45  1942.3 1941.87 1941.57 1942.56  1942.2 1942.11 1942.23
 1942.46 1944.03 1945.14 1949.29 1950.96 1951.79 1953.55 1955.61 1957.49  1960.3
 1961.05 1961.58 1961.75  1962.5  1962.9 1963.42 1964.82  1966.5 1968.43 1969.45
 1969.54 1969.47 1968.31 1967.39 1966.95 1965.35 1964.79 1964.74 1964.63 1964.77
 1964.77  1967.8  1953.5  1953.5  1950.4  1950.4  1947.3 1946.99 1945.37  1943.9
 1943.86 1943.27 1943.18 1942.74 1941.29 1941.27 1941.07 1940.63 1940.53 1940.71
                                                                                
                                                                                
                                                                                
                                                                                
          1953.1  1938.8  1938.8
                                                                                
Pier Skew, UpSta & Num, DnSta & Num=  ,386, 2 ,470, 2 , 0 , 0 , 0 ,,
       6       6
    1850    1955
       6       6
    1850    1955
Pier Skew, UpSta & Num, DnSta & Num=  ,687, 2 ,737, 2 , 0 , 0 , 0 ,,
       6       6
    1850    1955
       6       6
    1850    1955
BR Coef=-1 , 1 , 0 ,, 0 ,,,0.8,0,1.2,0,
WSPro=,,,, 1 ,,,, 0 ,,,, 0 ,,,,-1 ,-1 ,-1 , 0 , 0 , 0 , 0 , 0
BC Design=,, 0 ,, 0 ,,0,,,,
BC HTab HWMax=0
BC HTab TWMax=0
BC HTab MaxFlow=0
BC Use User HTab Curves=0
BC User HTab FreeFlow(D)= 0

Type RM Length L Ch R = 1 ,3189    ,126.4,124.6,121.8
BEGIN DESCRIPTION:
Merged US Survey DRC028BD
END DESCRIPTION:
XS GIS Cut Line= 4
     2172357.461      288694.821      2172639.94      289002.749
     2172802.811      289183.434     2173273.618      289709.086
#Sta/Elev= 30
       0 1942.03    29.4 1942.36    36.4  1945.4   61.311960.756    69.7 1963.05
   101.9 1967.15   124.6 1968.29   198.8 1965.68   302.2 1963.79   337.8 1948.45
  384.421918.341   469.6 1863.33   502.4 1862.58     508 1858.06     513 1855.92
   538.8  1855.3   555.4 1856.46   564.6 1855.47   571.7 1857.98   576.5  1861.4
   591.9 1865.77  619.891867.094   660.6 1869.69   682.8 1880.94   727.4 1910.05
   796.3 1938.77   805.1 1941.74   814.1 1943.45  1011.9 1938.22  1366.8 1935.78
#Mann= 6 ,-1 , 0
       0    .016       0   61.31     .12       0  384.42     .08       0
     508     .04       0   571.7     .12       0  619.89     .12       0
Bank Sta=508,571.7
XS Rating Curve= 0 ,0
Exp/Cntr=0.5,0.3

Type RM Length L Ch R = 1 ,3065    ,108.1,104.3,106.5
XS GIS Cut Line= 4
     2172247.119      288729.658     2172545.807      289089.567
     2172721.123      289268.594     2173200.003      289767.468
#Sta/Elev= 30
       0 1941.99    45.8 1939.88    66.8 1935.89    81.2  1940.1   106.8 1942.75
   145.1  1944.2   179.2 1941.34   234.7 1942.15     256 1939.03   292.8  1932.3
   383.9    1903   396.7 1896.98   413.7 1880.32   422.2 1874.96  453.861871.804
   524.4 1863.04   574.3 1861.45     581 1857.93   588.6  1853.6     616  1854.5
   629.9 1857.83   646.2 1865.54   700.2 1869.65  726.091868.968   771.1 1867.49
   808.6 1876.58   845.7 1883.26   903.7 1887.85  1131.1 1885.16  1409.6 1888.34
#Mann= 5 ,-1 , 0
       0     .12       0  453.86     .08       0     581     .04       0
   629.9     .08       0  726.09     .12       0
#Block Obstruct= 1 ,-1
  496.42  543.98 1872.95
Bank Sta=581,629.9
XS Rating Curve= 0 ,0
Exp/Cntr=0.5,0.3

Type RM Length L Ch R = 1 ,2960    ,54,52.2,52.3
BEGIN DESCRIPTION:
Merged DS Survey DRC022BU
END DESCRIPTION:
XS GIS Cut Line= 4
     2172123.749       288767.69     2172497.572      289187.892
     2172600.535      289293.639      2173090.89      289797.611
#Sta/Elev= 30
       0 1940.22    50.3 1938.35      69 1932.06     103  1925.4   120.5 1926.07
     141 1916.09   159.1 1911.86   307.2 1908.99   348.9 1896.84     362 1888.48
   370.8 1885.46   410.3 1883.04   427.9 1884.86   445.4 1892.39   459.4 1891.08
   491.9 1893.08   504.6 1888.68  535.031867.476   596.7 1866.14   610.8 1858.97
   624.4 1853.48   640.2 1852.41   656.5 1853.36  671.34 1858.91   683.9 1865.46
  912.541867.961  1081.3 1867.09  1097.6 1865.44  1338.9 1868.85  1413.1  1872.4
#Mann= 5 ,-1 , 0
       0     .12       0  535.03     .08       0   610.8     .04       0
  671.34     .08       0  912.54     .12       0
#XS Ineff= 2 , 0
             580 1866.29     695         1865.66
Permanent Ineff=
       F       F
#Block Obstruct= 1 ,-1
  544.83  574.42 1872.83
Bank Sta=610.8,671.34
XS Rating Curve= 0 ,0
Exp/Cntr=0.5,0.3