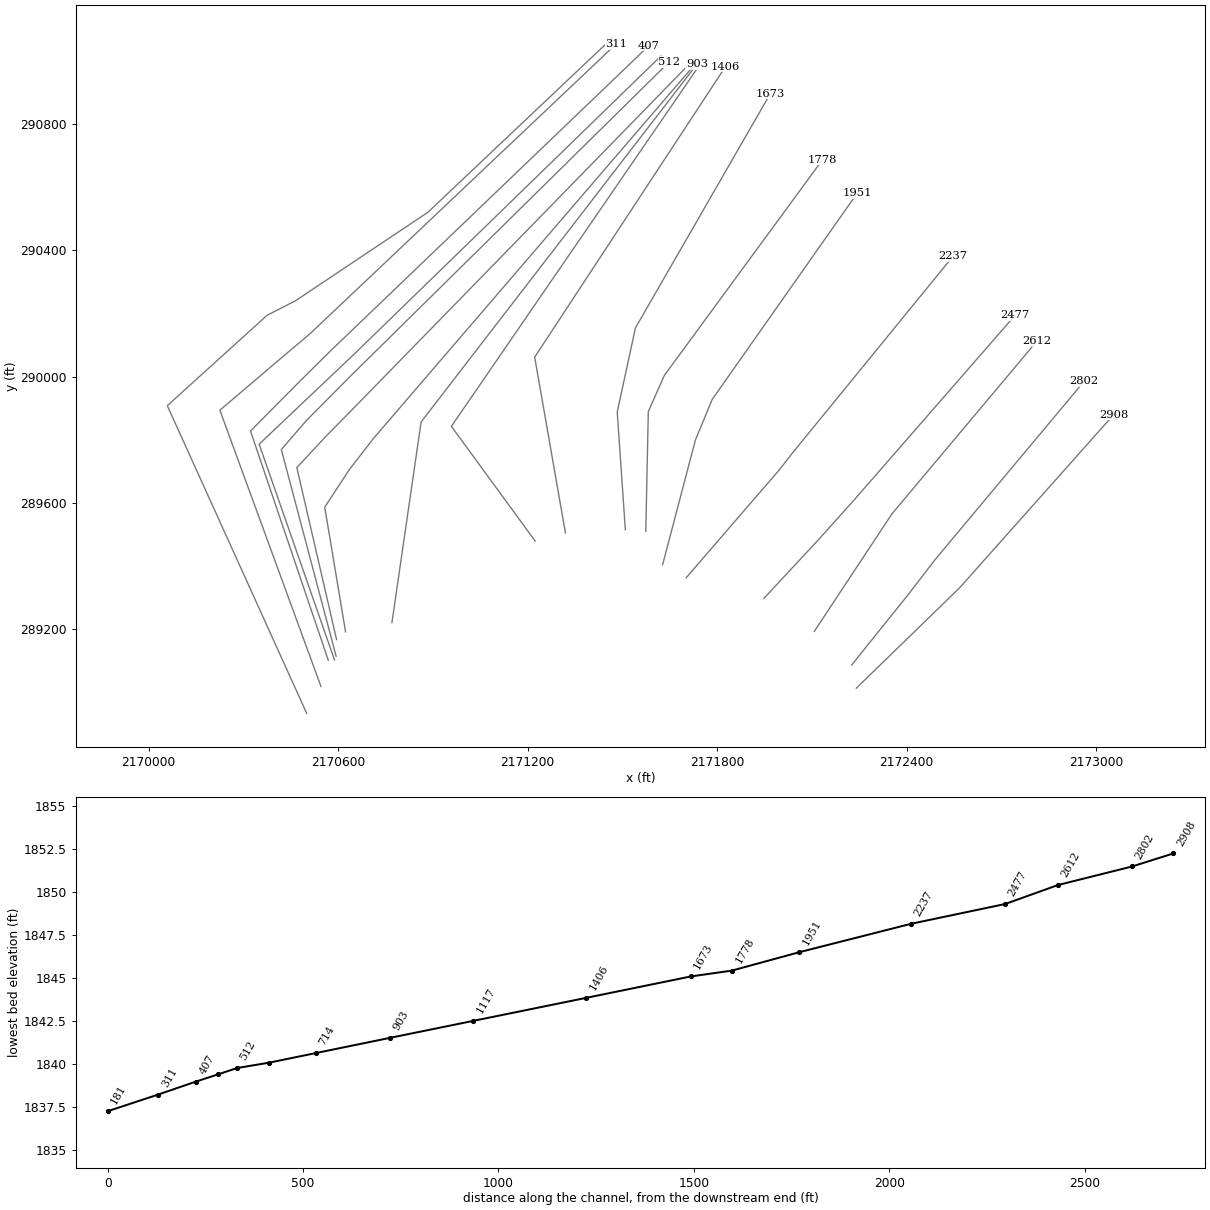
HEC-RAS study DRYCK1.prj: DRYCK1

--- DRYCK1.g01 (geometry) --- (continued)

Type RM Length L Ch R = 3 ,2935    ,,,
BEGIN DESCRIPTION:
Merged DS Survey DRC020RP- Gum st
END DESCRIPTION:
Bridge Culvert--1,0,-1,-1, 0
Deck Dist Width WeirC Skew NumUp NumDn MinLoCord MaxHiCord MaxSubmerge Is_Ogee
20,20,2.6,0, 60, 60, , , 0.98, 0, 0,0,,
       5    17.1    26.6    35.9      45   111.5   119.4   125.7   136.2   144.6
   168.1   184.4   210.7   229.6   263.9   300.4   305.2   314.1   318.6     346
   364.2   377.9   386.3   421.1   437.4   444.3   455.4   469.1   475.2   479.1
   482.8   494.1   516.2   527.1   532.4   537.5   574.2  598.28  598.28  683.42
  683.42  714.67  714.77   725.5   836.6   889.1   948.8  1036.2  1105.9  1130.9
  1140.7  1210.4  1237.2  1251.7  1333.9  1396.8  1411.3  1420.9  1430.6  1435.8
 1938.73 1939.12 1937.51 1933.21 1930.49 1917.16 1917.03 1915.95 1910.79 1909.15
 1907.75 1905.86 1905.78 1904.97 1905.41 1895.14 1894.42  1891.1 1889.98 1888.94
 1887.29 1887.67 1889.31 1899.75  1899.7 1900.87 1904.32  1905.2    1905 1904.43
 1903.06 1897.17 1881.88 1870.83  1867.6 1866.76 1865.38 1865.38 1868.98 1868.98
 1865.38 1865.38 1866.06  1866.3 1867.54 1867.21 1867.65 1866.23 1866.75 1866.38
 1867.26 1867.42 1868.14 1867.49 1867.52 1868.92 1870.66 1871.16 1871.29 1870.82
                                                                                
                                                                                
                                                                                
                                                                 1862.68 1862.65
                                                                                
                                                                                
    -255  -242.9  -233.4  -224.1    -215  -148.5  -140.6  -134.3  -123.8  -115.4
   -91.9   -75.6   -49.3   -30.4     3.9    40.4    45.2    54.1    58.6      86
   104.2   117.9   126.3   161.1   165.7   177.4   184.3   195.4   209.1   215.2
   219.1   222.8   234.1   256.2   267.1   272.4   277.5   314.2  340.88  340.88
   390.5  426.02  426.02   514.6   576.6   629.1   688.8   776.2   845.9   870.9
   880.7   950.4   977.2   991.7  1073.9  1136.8  1151.3  1160.9  1170.6  1175.8
 1938.73 1939.12 1937.51 1933.21 1930.49 1917.16 1917.03 1915.95 1910.79 1909.15
 1907.75 1905.86 1905.78 1904.97 1905.41 1895.14 1894.42  1891.1 1889.98 1888.94
 1887.29 1887.67 1889.31 1899.75 1900.08  1899.7 1900.87 1904.32  1905.2    1905
 1904.43 1903.06 1897.17 1881.88 1870.83  1867.6 1866.76 1865.38 1865.38 1868.98
 1868.98 1868.98 1865.38 1867.06 1867.54 1867.21 1867.65 1866.23 1866.75 1866.38
 1867.26 1867.42 1868.14 1867.49 1867.52 1868.92 1870.66 1871.16 1871.29 1870.82
                                                                                
                                                                                
                                                                                
                                                                          1862.7
 1862.76 1862.76
                                                                                
BR Coef=-1 , 1 , 0 ,, 0 ,,,0.8,0,1.2,0,
WSPro=,,,, 1 ,,,, 0 ,,,, 0 ,,,,-1 ,-1 ,-1 , 0 , 0 , 0 , 0 , 0
BC Design=,, 0 ,, 0 ,,0,,,,
BC HTab HWMax=0
BC HTab TWMax=0
BC HTab MaxFlow=0
BC Use User HTab Curves=0
BC User HTab FreeFlow(D)= 0

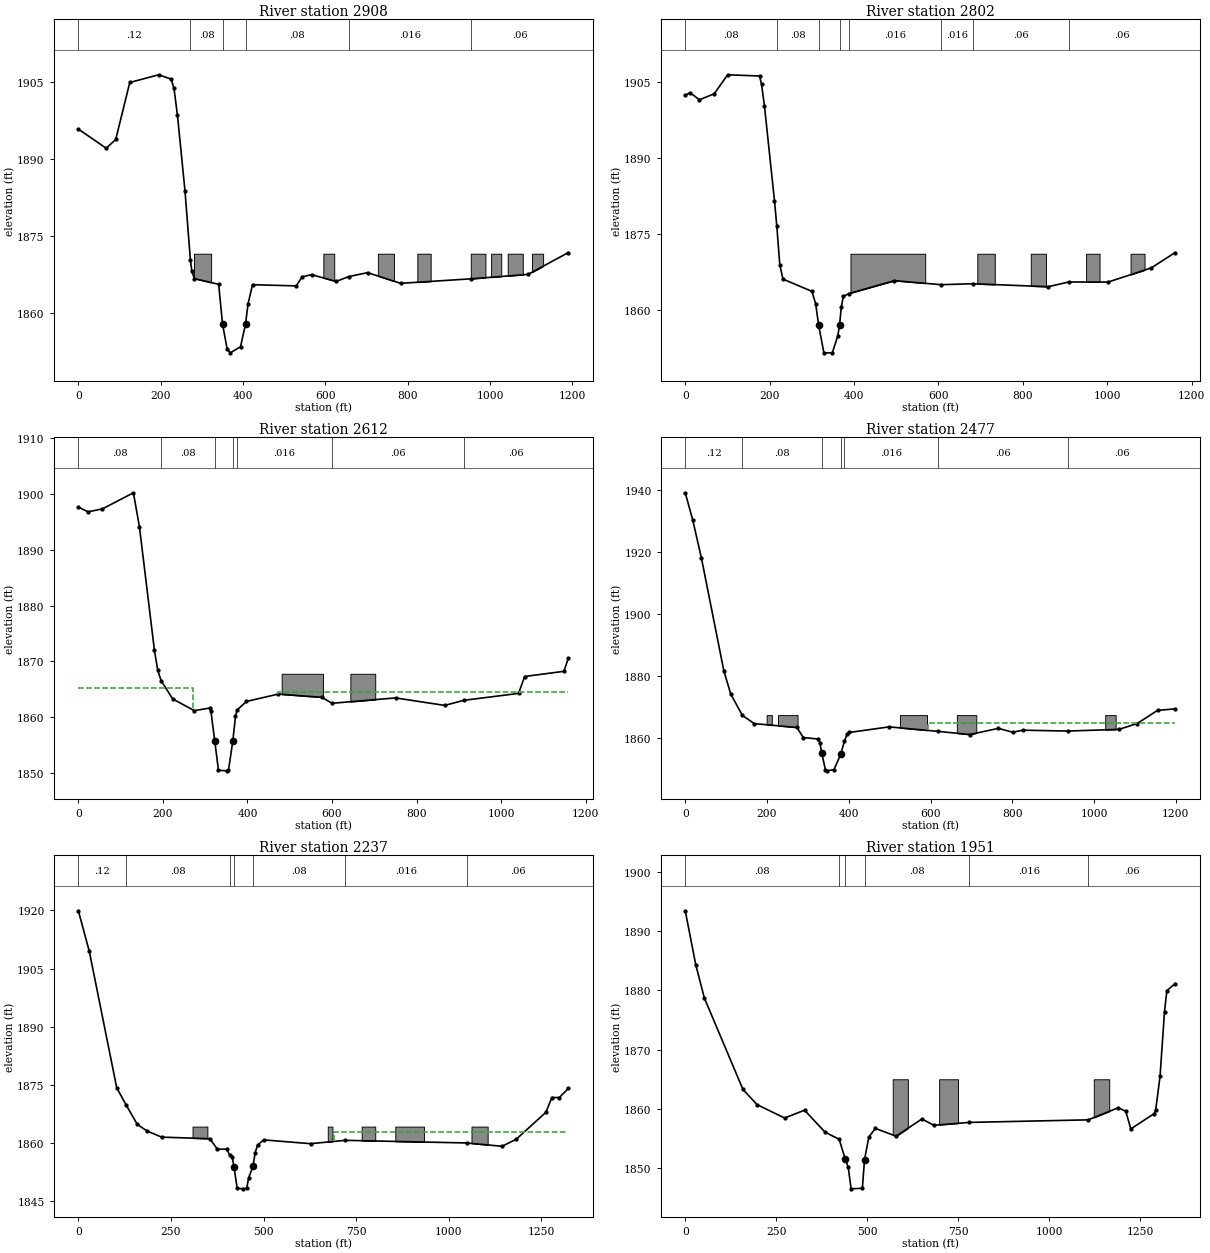
Type RM Length L Ch R = 1 ,2908    ,102.8,105.8,110.2
BEGIN DESCRIPTION:
Merged US Survey DRC018BD
END DESCRIPTION:
XS GIS Cut Line= 3
     2172240.626      289013.504     2172567.142      289330.743
     2173055.554       289879.66
#Sta/Elev= 30
       0 1895.76    67.6 1892.03    90.8 1893.74   124.9 1904.81   195.2 1906.31
   225.4 1905.47   232.3 1903.66   240.7 1898.44     259 1883.74  272.071870.394
   275.5 1868.18   281.8 1866.69   340.8 1865.58  350.151857.875   361.3 1853.06
   369.2 1852.26   393.9 1853.45  406.08 1857.88   412.1 1861.75     423 1865.51
   529.1 1865.27   543.4 1867.03   566.6 1867.46   625.8 1866.14  656.961867.083
   702.5 1867.85   782.7 1865.77  953.461866.648  1092.4 1867.51    1190 1871.75
#Mann= 6 ,-1 , 0
       0     .12       0  272.07     .08       0  350.15     .04       0
  406.08     .08       0  656.96    .016       0  953.46     .06       0
#XS Ineff= 2 , 0
           335.8  1864.4     431          1864.4
Permanent Ineff=
       F       F
#Block Obstruct= 8 ,-1
     281  322.51 1871.53     595  621.51 1871.53  727.42  766.48 1871.53
  823.32  855.69 1871.53  953.15   988.7 1871.53 1002.52 1027.16 1871.53
 1042.76 1079.47 1871.53 1101.91 1128.82 1871.53
Bank Sta=350.15,406.08
XS Rating Curve= 0 ,0
Exp/Cntr=0.5,0.3

Type RM Length L Ch R = 1 ,2802    ,189.1,190,191.7
XS GIS Cut Line= 4
     2172225.622      289086.646     2172403.211       289307.71
     2172489.921      289420.429     2172961.336      289984.464
#Sta/Elev= 30
       0 1902.32    11.4 1902.85    33.6 1901.44    68.6 1902.63   100.5 1906.38
     176 1906.14   180.7 1904.56   187.7 1900.18   211.4 1881.56  216.821876.596
     224  1868.9   231.5 1866.05     300 1863.64   309.1 1861.17     316 1856.96
   328.5  1851.5   348.5  1851.5   361.6 1854.92   365.7 1857.07   369.9 1860.63
   374.6 1862.63  387.511863.197   495.5 1865.75  606.211864.951  680.671865.142
   859.7 1864.55  908.821865.482    1002 1865.47  1103.8 1868.25  1160.9  1871.3
#Mann= 8 ,-1 , 0
       0     .08       0  216.82     .08       0     316     .04       0
   365.7     .12       0  387.51    .016       0  606.21    .016       0
  680.67     .06       0  908.82     .06       0
#Block Obstruct= 5 ,-1
  391.44  568.62 1871.06     692   733.4 1871.06  818.71  854.74 1871.06
  949.79  981.68 1871.06 1055.16  1088.3 1871.06
Bank Sta=316,365.7
XS Rating Curve= 0 ,0
Exp/Cntr=0.3,0.1

Type RM Length L Ch R = 1 ,2612    ,138.6,134.8,130.1
XS GIS Cut Line= 3
      2172107.44      289193.163     2172352.979       289564.85
     2172811.531      290111.363
#Sta/Elev= 30
       0 1897.63    22.7 1896.77    56.8 1897.29   130.2 1900.18   144.4 1894.13
   179.9 1872.01   187.8 1868.43  195.891866.531   223.2 1863.29   274.3 1861.19
   310.7 1861.66   313.6 1861.11   322.6 1855.78   331.4 1850.52   352.4 1850.42
   355.1 1850.52   365.3 1855.72   371.7 1860.16  375.241861.295   397.7 1862.84
   472.9 1864.16     576 1863.58  599.891862.509   750.2 1863.47   866.6 1862.13
  912.021863.045  1041.3 1864.28  1055.6  1867.3  1148.4 1868.23  1158.9 1870.53
#Mann= 7 ,-1 , 0
       0     .08       0  195.89     .08       0   322.6    .045       0
   365.3     .12       0  375.24    .016       0  599.89     .06       0
  912.02     .06       0
#XS Ineff= 2 , 0
           271.2 1865.27   472.7         1864.51
Permanent Ineff=
       F       F
#Block Obstruct= 2 ,-1
  480.92  578.67 1867.79  643.42  702.23 1867.79
Bank Sta=322.6,365.3
XS Rating Curve= 0 ,0
Exp/Cntr=0.3,0.1

Type RM Length L Ch R = 1 ,2477    ,244.3,240.8,243.1
XS GIS Cut Line= 4
     2171947.979      289297.818     2172121.811      289484.704
     2172234.618      289610.481      2172743.45      290194.272
#Sta/Elev= 30
       0 1939.25    18.4 1930.39    39.7 1918.06    94.4 1881.66   111.4 1874.11
  139.731867.255   168.7 1864.59   273.2 1863.35   288.8 1860.09   325.3 1859.61
   329.7 1858.17   334.1 1854.93   342.8 1849.72   347.2 1849.32   363.8 1849.72
   380.1 1854.61  389.491858.946   395.8 1861.19     401 1861.72   498.6 1863.54
  617.761862.098     696 1861.06     766 1863.06   800.9 1861.81   825.9 1862.47
  935.391862.189  1061.3 1862.73  1105.6 1864.63  1155.4 1868.87  1198.6 1869.37
#Mann= 7 ,-1 , 0
       0     .12       0  139.73     .08       0   334.1     .04       0
   380.1     .12       0  389.49    .016       0  617.76     .06       0
  935.39     .06       0
#XS Ineff= 2 , 0
                           593.4         1864.72
Permanent Ineff=
       F       F
#Block Obstruct= 5 ,-1
  199.08  211.81 1867.34  226.86  274.68 1867.34  525.14  591.47 1867.34
  664.41  711.98 1867.34 1027.38 1052.92 1867.34
Bank Sta=334.1,380.1
XS Rating Curve= 0 ,0
Exp/Cntr=0.3,0.1

Type RM Length L Ch R = 1 ,2237    ,276.1,285.9,293
XS GIS Cut Line= 4
     2171702.092      289363.284     2171996.273      289704.005
     2172039.697      289759.623     2172546.844      290381.034
#Sta/Elev= 30
       0  1919.9    29.5 1909.46   103.6 1874.24  128.971869.799   159.4 1864.77
   185.3 1863.11   224.7 1861.51     355  1861.1   375.3 1858.39   400.4 1858.41
  408.141856.957   415.6 1856.31   420.1 1853.89   428.7 1848.31   445.2 1848.17
   454.5 1848.31   459.8 1851.04   471.5 1853.95   477.3 1857.47   483.7 1859.43
   500.3  1860.8     627 1859.82  720.971860.683  1048.71860.002  1143.7 1859.15
  1181.8 1860.94    1262 1867.89  1278.4 1871.73  1298.3 1871.71  1322.7 1874.06
#Mann= 7 ,-1 , 0
       0     .12       0  128.97     .08       0  408.14     .12       0
   420.1     .04       0   471.5     .08       0  720.97    .016       0
  1048.7     .06       0
#XS Ineff= 2 , 0
                           689.3         1862.71
Permanent Ineff=
       F       F
#Block Obstruct= 6 ,-1
  308.25  348.33 1864.23  673.28  685.98 1864.23  764.99  801.53 1864.23
  855.69  933.02 1864.23 1061.34 1104.96 1864.23 1229.78 1260.87 1864.23
Bank Sta=420.1,471.5
XS Rating Curve= 0 ,0
Exp/Cntr=0.3,0.1

Type RM Length L Ch R = 1 ,1951    ,157.9,172.8,173
XS GIS Cut Line= 4
     2171627.204      289404.071     2171731.173      289799.411
      2171784.12      289927.446     2172243.919      290581.263
#Sta/Elev= 30
       0 1893.44    28.8 1884.35    52.5 1878.72   158.6 1863.29   197.4 1860.73
     273 1858.47   327.9 1859.79   384.3 1856.08   422.9 1854.89   439.9 1851.53
  448.04 1850.15   455.8 1846.52   486.8 1846.62  492.68 1851.43   504.6 1855.25
   522.3 1856.72   579.6  1855.4   650.3 1858.31   683.2 1857.25  780.271857.729
 1107.341858.162  1190.4 1860.21  1210.7 1859.61  1224.6 1856.63  1289.2 1859.23
  1293.1 1859.89  1304.9 1865.49  1317.2 1876.42  1323.7 1879.97  1346.6 1881.16
#Mann= 6 ,-1 , 0
       0     .08       0   422.9     .12       0   439.9     .04       0
  492.68     .08       0  780.27    .016       0 1107.34     .06       0
#Block Obstruct= 3 ,-1
  570.24  611.78 1865.01  697.83   749.5 1865.01 1122.75 1165.31 1865.01
Bank Sta=439.9,492.68
XS Rating Curve= 0 ,0
Exp/Cntr=0.3,0.1

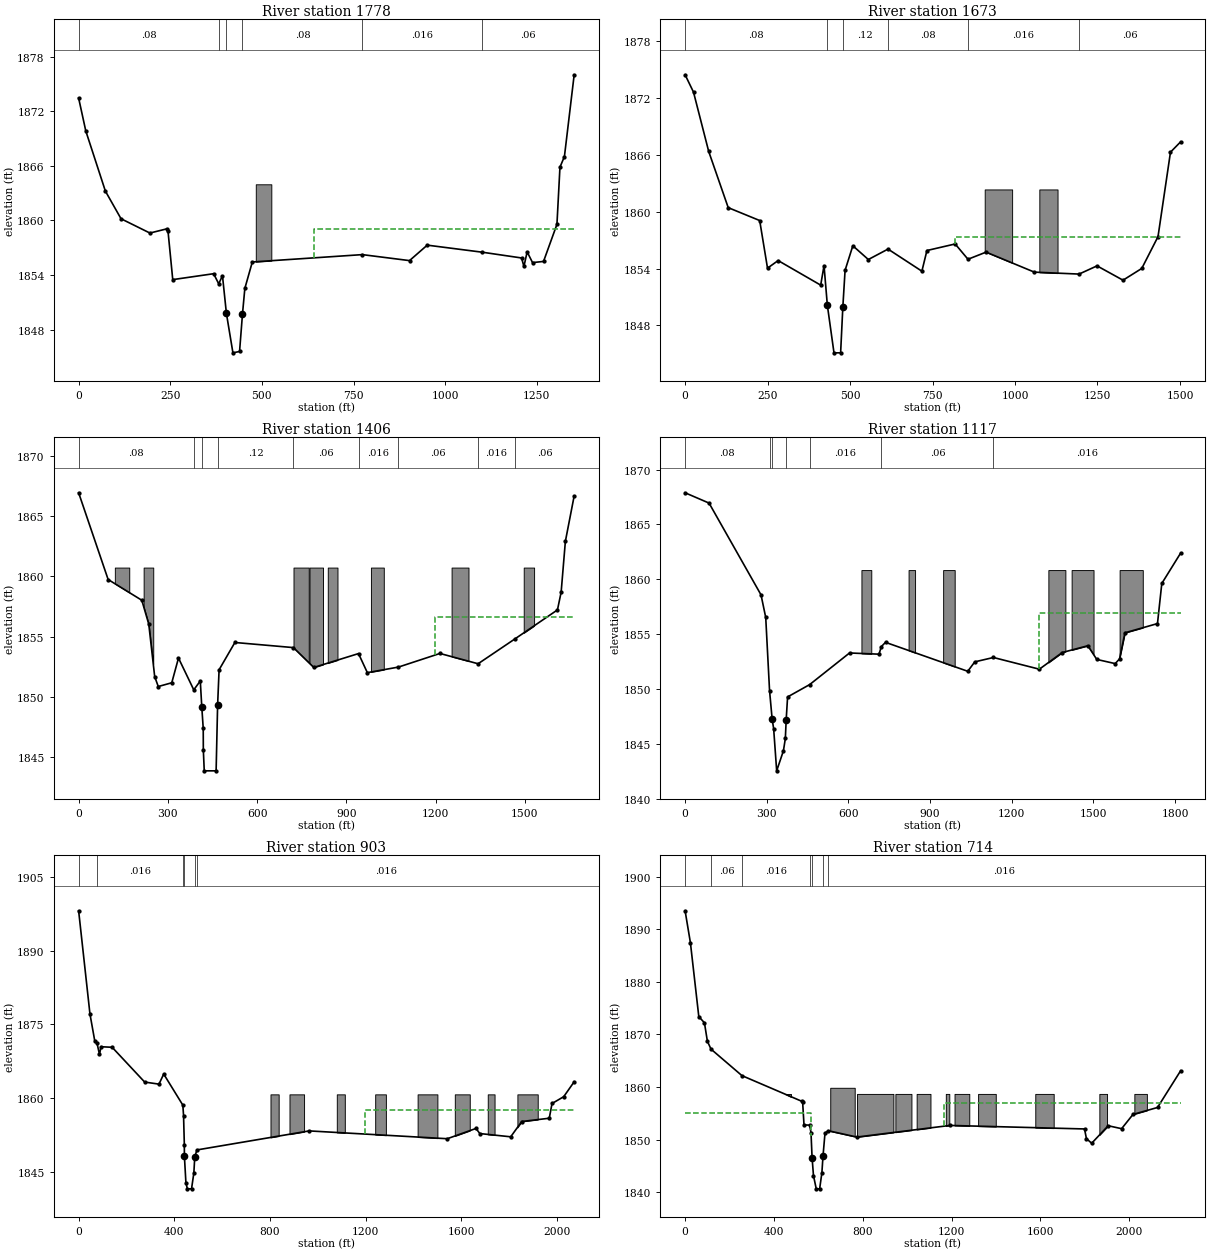
Type RM Length L Ch R = 1 ,1778    ,95,105,113.8
XS GIS Cut Line= 4
     2171573.954      289509.774     2171581.935      289888.871
     2171632.481      290003.265     2172133.954      290686.971
#Sta/Elev= 30
       0 1873.46    19.5 1869.85      73 1863.23   115.7 1860.19   194.5 1858.62
   240.4 1859.08   243.7  1858.9   256.8  1853.5   368.4 1854.15  382.131853.043
   392.5 1853.92   403.2 1849.79     421 1845.45   439.1  1845.6   447.1 1849.73
   453.5 1852.53   473.9 1855.44  774.061856.248   902.8 1855.59   951.2 1857.29
 1101.591856.512  1208.6 1855.88    1215 1854.95  1223.8 1856.55  1238.5 1855.37
  1268.5  1855.5  1305.1 1859.58  1313.3 1865.86  1325.5 1867.03  1352.1 1876.02
#Mann= 6 ,-1 , 0
       0     .08       0  382.13     .12       0   403.2    .035       0
   447.1     .08       0  774.06    .016       0 1101.59     .06       0
#XS Ineff= 2 , 0
                          642.56         1859.03
Permanent Ineff=
       F       F
#Block Obstruct= 2 ,-1
  483.36  525.78 1863.98 1320.98 1348.29 1863.98
Bank Sta=403.2,447.1
XS Rating Curve= 0 ,0
Exp/Cntr=0.3,0.1

Type RM Length L Ch R = 1 ,1673    ,229.1,266.8,273.7
XS GIS Cut Line= 4
     2171509.303      289514.734     2171483.503      289887.541
     2171541.201      290153.922     2171968.121      290895.543
#Sta/Elev= 30
       0 1874.43    25.5  1872.6    71.5 1866.35   130.7 1860.42   226.1 1859.06
   249.8 1854.04     282 1854.84     411 1852.25   421.1 1854.31   431.2 1850.12
   451.3 1845.11   471.4 1845.11   478.1 1849.93   484.9 1853.81   508.4  1856.4
   555.4 1854.95   615.1 1856.05   717.7 1853.72     733  1855.9   818.6 1856.59
  857.411854.978   912.3 1855.73  1058.6 1853.62 1194.131853.415  1248.6 1854.28
  1327.4 1852.77  1384.2 1854.01  1433.4 1857.36  1471.2 1866.27    1502 1867.36
#Mann= 6 ,-1 , 0
       0     .08       0   431.2    .035       0   478.1     .12       0
   615.1     .08       0  857.41    .016       0 1194.13     .06       0
#XS Ineff= 2 , 0
                          818.24         1857.29
Permanent Ineff=
       F       F
#Block Obstruct= 3 ,-1
       0   31.39 1862.34  908.11  991.26 1862.34 1073.68 1128.88 1862.34
Bank Sta=431.2,478.1
XS Rating Curve= 0 ,0
Exp/Cntr=0.3,0.1

Type RM Length L Ch R = 1 ,1406    ,251.5,289.6,305.1
XS GIS Cut Line= 3
     2171319.573      289504.768      2171222.21      290061.438
     2171826.502      290981.515
#Sta/Elev= 30
       0 1866.92    99.2 1859.73   212.4 1858.01   235.8 1856.03   255.7 1851.68
   267.7 1850.86   313.1 1851.17   335.7 1853.22  387.061850.585     409 1851.32
  414.02 1849.16   418.9 1847.38   419.2 1845.62   422.3 1843.87   462.2 1843.87
  467.21 1849.31   472.2 1852.25   525.3 1854.51  722.061854.086   790.5 1852.44
  940.87 1853.59   970.6 1852.01 1075.241852.472  1214.6  1853.6 1342.941852.747
  1466.31854.799  1609.7 1857.21  1622.1 1858.68  1636.3 1862.89  1665.9 1866.66
#Mann= 9 ,-1 , 0
       0     .08       0  387.06     .12       0  414.02    .035       0
  467.21     .12       0  722.06     .06       0  940.87    .016       0
 1075.24     .06       0 1342.94    .016       0  1466.3     .06       0
#XS Ineff= 2 , 0
                         1198.98         1856.66
Permanent Ineff=
       F       F
#Block Obstruct= 9 ,-1
  121.69  170.16 1860.72  218.55  250.86 1860.72  722.33  773.55 1860.72
  776.07  821.57 1860.72  837.55  870.23 1860.72  982.63 1025.87 1860.72
 1253.79 1310.64 1860.72 1496.29  1531.2 1860.72 1637.42 1659.79 1860.72
Bank Sta=414.02,467.21
XS Rating Curve= 0 ,0
Exp/Cntr=0.3,0.1

Type RM Length L Ch R = 1 ,1117    ,227.3,213.9,135.7
XS GIS Cut Line= 3
     2171223.884      289478.949     2170958.451      289842.283
     2171734.395      290971.857
#Sta/Elev= 30
       0 1867.89      88 1866.95   278.9 1858.58   296.2 1856.52  310.241849.855
   319.7 1847.26   325.3 1846.38   336.4 1842.53   361.2 1844.36   368.3 1845.48
   371.3 1847.17   376.5 1849.27  457.561850.396   604.1 1853.28   712.3 1853.17
  720.941853.863   736.2 1854.25  1038.3 1851.61  1064.2 1852.47 1132.661852.867
  1301.4  1851.8  1385.3 1853.32  1479.5 1853.94  1512.4 1852.69    1580 1852.31
  1595.9 1852.74  1615.8 1855.12  1735.3 1855.96  1751.2 1859.62  1820.4 1862.39
#Mann= 7 ,-1 , 0
       0     .08       0  310.24     .12       0   319.7     .04       0
   371.3     .12       0  457.56    .016       0  720.94     .06       0
 1132.66    .016       0
#XS Ineff= 2 , 0
                         1301.64         1856.92
Permanent Ineff=
       F       F
#Block Obstruct= 9 ,-1
    8.35   40.27 1860.84   48.39   85.17 1860.84  110.53  121.22 1860.84
  647.78  683.98 1860.84  820.95  844.83 1860.84  947.95  990.38 1860.84
  1334.5 1396.99 1860.84 1419.94 1500.42 1860.84 1596.26 1681.32 1860.84
Bank Sta=319.7,371.3
XS Rating Curve= 0 ,0
Exp/Cntr=0.3,0.1

Type RM Length L Ch R = 1 ,903     ,197.1,188.7,149.7
XS GIS Cut Line= 3
     2170770.316      289221.047     2170862.675      289856.293
     2171735.336      290988.067
#Sta/Elev= 30
       0 1898.13    47.3 1877.14    67.2  1871.7   77.011871.144    87.1 1868.91
    93.7 1870.46   140.1 1870.35     276 1863.27   335.8 1862.85   355.6  1864.9
  435.541858.577   438.5 1856.46   441.8 1850.54  442.03 1848.19   448.4 1842.78
   454.5 1841.54   471.9 1841.54   481.6 1844.79  485.41 1848.07   494.6 1849.46
   963.6 1853.33  1540.8 1851.74  1660.7 1853.83  1676.8 1852.79  1805.8 1852.13
  1851.9 1855.24    1967 1855.91  1978.6 1858.91  2027.3 1860.29  2071.1 1863.33
#Mann= 6 ,-1 , 0
       0     .12       0   77.01    .016       0  435.54     .12       0
  442.03     .04       0  485.41     .12       0   494.6    .016       0
#XS Ineff= 2 , 0
                         1198.93         1857.58
Permanent Ineff=
       F       F
#Block Obstruct= 10 ,-1
  158.77  166.15 1860.77   212.5  310.15 1860.77  801.86  836.05 1860.77
  881.22  942.22 1860.77 1078.99 1112.51 1860.77 1239.43 1284.15 1860.77
 1416.76 1499.47 1860.77  1572.2 1634.69 1860.77 1709.91 1738.38 1860.77
 1833.85 1918.77 1860.77
Bank Sta=442.03,485.41
XS Rating Curve= 0 ,0
Exp/Cntr=0.3,0.1

Type RM Length L Ch R = 1 ,714     ,123.9,120.3,113.5
XS GIS Cut Line= 5
     2170623.439      289191.806     2170557.494      289586.435
     2170636.212      289706.355     2170711.022      289803.062
     2171731.373      290990.519
#Sta/Elev= 30
       0  1893.5    23.9 1887.44    61.7 1873.39    87.1 1872.21   100.4  1868.7
  116.811867.203  256.071862.171   526.9 1857.27   529.3 1857.12   535.4 1852.81
  560.781852.765   566.9 1851.35  571.78  1846.6   578.1 1843.17   590.6 1840.66
   605.9 1840.66     616 1843.74  620.98 1846.87     630 1851.26  644.671851.704
   773.4  1850.5    1193 1852.71  1798.5 1852.04  1807.2 1850.21  1830.7 1849.32
  1905.2 1852.65  1965.6 1852.09  2016.8  1854.8  2127.3 1856.12  2231.4  1863.1
#Mann= 7 ,-1 , 0
       0     .12       0  116.81     .06       0  256.07    .016       0
  560.78     .12       0  571.78     .04       0  620.98    .016       0
  644.67    .016       0
#XS Ineff= 2 , 0
           567.6 1855.05 1165.91         1857.04
Permanent Ineff=
       F       F
#Block Obstruct= 12 ,-1
  170.56  196.26  1858.7   284.1  478.07  1858.7  653.57  763.761859.864
   774.2  937.96  1858.7  946.94 1019.22  1858.7 1042.66 1104.92  1858.7
 1173.99 1189.71  1858.7 1213.21 1279.68  1858.7  1319.4 1398.96  1858.7
 1576.86 1659.75  1858.7 1865.38 1900.06  1858.7 2022.98 2079.35  1858.7
Bank Sta=571.78,620.98
XS Rating Curve= 0 ,0
Exp/Cntr=0.5,0.3

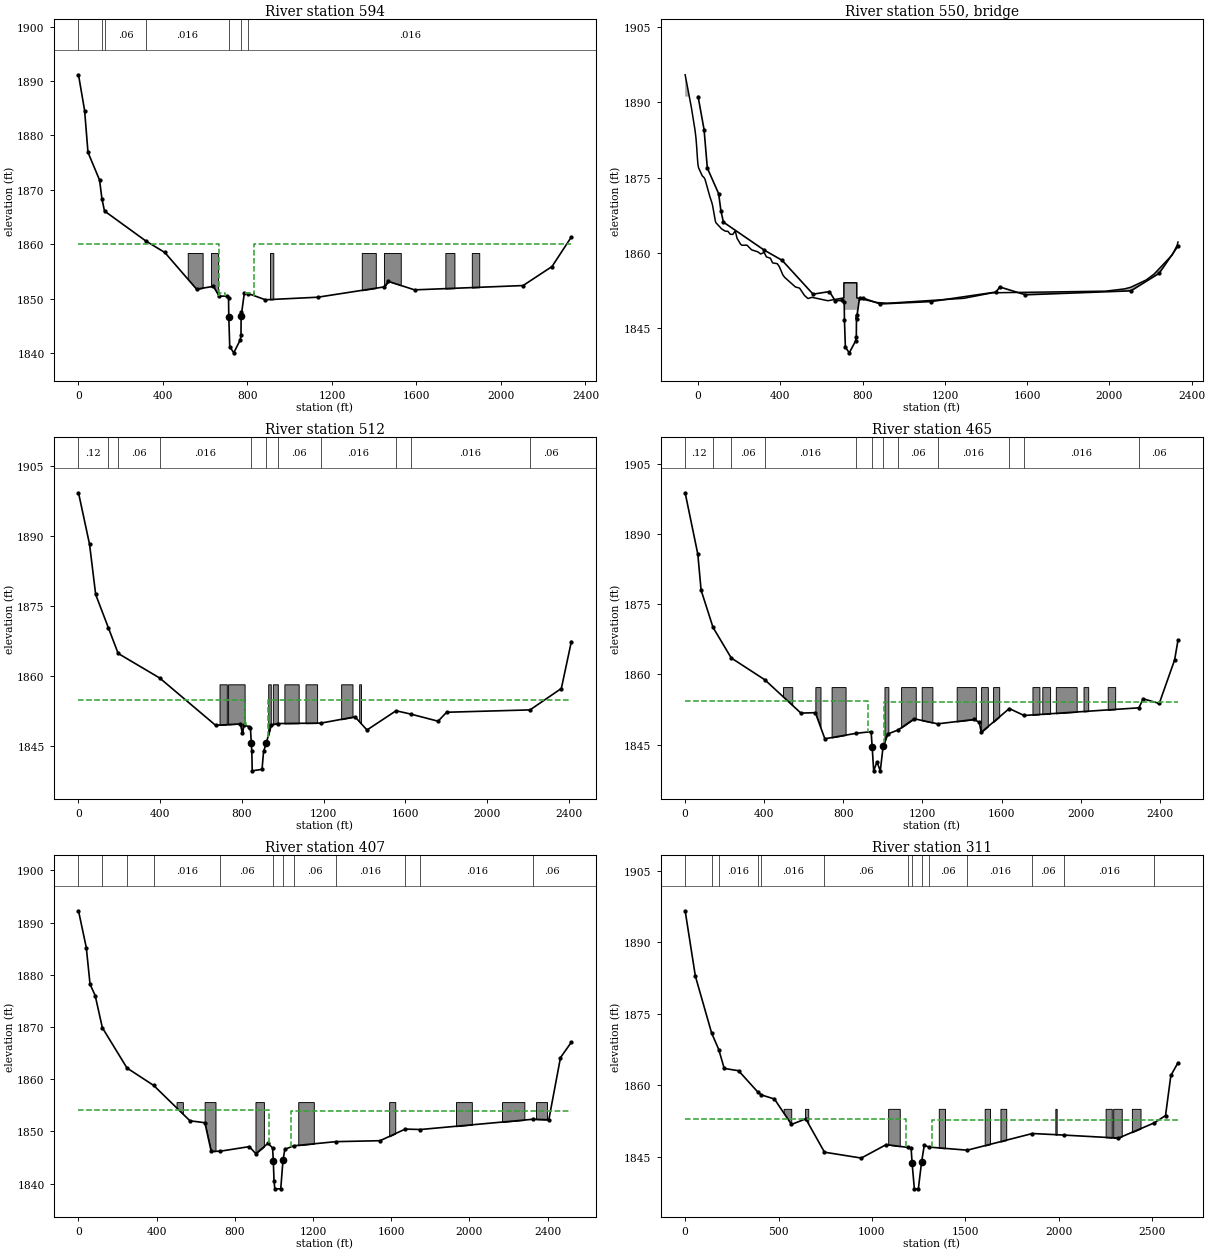
Type RM Length L Ch R = 1 ,594     ,82.3,81.5,80.2
BEGIN DESCRIPTION:
Merged DS Survey DRC012BU
END DESCRIPTION:
XS GIS Cut Line= 5
     2170594.975      289167.355     2170469.115       289711.89
     2170564.605      289814.148      2170647.16      289897.943
     2171706.287      290983.703
#Sta/Elev= 30
       0 1891.14      29 1884.56    44.9  1876.9    99.8 1871.81  110.961868.378
  123.111866.133   320.81860.579   408.7 1858.52   558.9 1851.79   638.5  1852.3
   666.2 1850.49     701 1850.53   710.3 1850.18  711.46 1846.73     716 1841.24
   734.9  1840.1   765.6 1842.46   769.2 1843.29   770.1 1847.58  770.18 1846.83
   785.1 1851.09   803.8 1850.98   884.9 1849.84  1132.4 1850.31  1448.1 1852.21
    1467 1853.22  1590.8 1851.66  2104.6 1852.45  2241.6 1855.94  2333.2 1861.37
#Mann= 7 ,-1 , 0
       0     .12       0  110.96    .016       0  123.11     .06       0
   320.8    .016       0  711.46    .035       0  770.18     .12       0
   803.8    .016       0
#XS Ineff= 4 ,-1
       0     665    1860     665  693.93 1851.05   786.6     830 1851.05
     830    2500    1860
Permanent Ineff=
       F       F       F       F
#Block Obstruct= 10 ,-1
  196.42  208.14 1858.43  348.38  360.75 1858.43  391.02  410.05 1858.43
  517.13  587.65 1858.43  627.16  660.45 1858.43  906.46  922.18 1858.43
 1341.17 1407.36 1858.43 1446.01 1525.64 1858.43 1736.73 1779.66 1858.43
 1861.96 1897.04 1858.43
Bank Sta=711.46,770.18
XS Rating Curve= 0 ,0
Exp/Cntr=0.5,0.3

Type RM Length L Ch R = 3 ,550     ,,,
BEGIN DESCRIPTION:
Merged DS Survey DRC010RP- Main St E
END DESCRIPTION:
Bridge Culvert--1,0,-1,-1, 0
Deck Dist Width WeirC Skew NumUp NumDn MinLoCord MaxHiCord MaxSubmerge Is_Ogee
8,50,2.6,0, 60, 60, , , 0.98, 0, 0,0,,
     -63  -32.99     -15   -10.5    -7.1    -3.3     -.6     2.1      20    30.1
    34.6    57.2    67.3    70.7    84.2    87.6   114.7   131.6   145.1   156.2
   168.8   178.9   182.3   189.1     206     213   237.4   260.1   290.6   304.1
     321     332   351.5   362.2   385.3   395.4   412.4   421.2   472.6   493.5
   517.2   534.1   553.7   630.8  708.68  708.68   771.6   771.6     870   921.5
    1292  1431.1  1981.3  2073.2  2104.3  2178.7  2216.4  2305.8  2329.3  2333.2
 1895.49 1889.04 1884.46 1882.94 1881.22 1878.82 1877.56 1876.98 1875.37 1874.96
 1874.53 1871.21 1869.97 1869.39 1866.27 1865.97 1864.78 1864.35  1864.3 1863.72
 1863.69 1864.31 1864.13 1862.94 1861.77 1861.53 1861.55 1860.62 1860.21 1859.79
  1860.1 1859.22 1858.94 1858.02 1857.85 1857.22 1855.59 1855.12 1853.24 1852.98
 1851.53 1850.92 1851.16 1850.48 1851.05 1854.05 1854.05 1851.05 1850.12 1849.98
 1850.96 1852.06 1852.39 1852.84 1853.18 1854.62 1855.77 1859.64 1861.55 1862.17
                                                                                
                                                                                
                                                                                
                                                                                
                                         1848.66 1848.66
                                                                                
    73.5   103.5  103.51   121.5     126   129.4   133.2   135.9   138.6   156.5
   166.6   171.1   193.7   203.8   207.2   220.7   224.1   251.2   281.6   292.7
   305.3   315.4   318.8   325.6   342.5   349.5   373.9   396.6   427.1   440.6
   457.5   468.5     488   498.7   521.8   531.9   548.9   557.7   609.1     630
   653.7   670.6   690.2   767.3  845.18  845.18   908.1   908.1  1006.5    1058
  1428.5  1567.6  2117.8  2209.7  2240.8  2315.2  2352.9  2442.3  2465.8  2469.7
 1895.49 1889.48 1889.04 1884.46 1882.94 1881.22 1878.82 1877.56 1876.98 1875.37
 1874.96 1874.53 1871.21 1869.97 1869.39 1866.27 1865.97 1864.78  1864.3 1863.72
 1863.69 1864.31 1864.13 1862.94 1861.77 1861.53 1861.55 1860.62 1860.21 1859.79
  1860.1 1859.22 1858.94 1858.02 1857.85 1857.22 1855.59 1855.12 1853.24 1852.98
 1851.53 1850.92 1851.16 1850.48 1851.05 1854.05 1854.05 1851.05 1850.12 1849.98
 1850.96 1852.06 1852.39 1852.84 1853.18 1854.62 1855.77 1859.64 1861.55 1862.17
                                                                                
                                                                                
                                                                                
                                                                                
                                         1848.66 1848.66
                                                                                
BR Coef=-1 , 1 , 0 ,, 0 ,,,0.8,0,1.2,0,
WSPro=,,,, 1 ,,,, 0 ,,,, 0 ,,,,-1 ,-1 ,-1 , 0 , 0 , 0 , 0 , 0
BC Design=,, 0 ,, 0 ,,0,,,,
BC HTab HWMax=0
BC HTab TWMax=0
BC HTab MaxFlow=0
BC Use User HTab Curves=0
BC User HTab FreeFlow(D)= 0

Type RM Length L Ch R = 1 ,512     ,49,47.5,45
BEGIN DESCRIPTION:
Merged US Survey DRC008BD
END DESCRIPTION:
XS GIS Cut Line= 5
       2170593.6      289114.368     2170420.094      289768.842
     2170498.434      289859.619       2170638.5      290000.883
     2171647.697      290995.714
#Sta/Elev= 30
       0  1899.3    54.1 1888.28    84.1 1877.53  146.141870.422  194.221864.914
  397.69 1859.65   671.1 1849.54   792.9 1849.84     802 1847.83   809.1 1849.59
   836.8 1849.24   841.9 1848.94  846.02 1845.65   848.6 1843.94   850.5 1839.79
   898.6 1840.11   906.1 1843.93     920  1845.8   943.1 1849.62   975.4 1849.91
 1187.211850.007  1353.8 1851.35  1412.4 1848.53 1554.851852.648 1627.261851.933
  1760.4 1850.41  1802.4 1852.33 2210.741852.833  2363.9 1857.41    2413 1867.45
#Mann= 11 ,-1 , 0
       0     .12       0  146.14    .016       0  194.22     .06       0
  397.69    .016       0  846.02    .035       0     920    .016       0
   975.4     .06       0 1187.21    .016       0 1554.85     .06       0
 1627.26    .016       0 2210.74     .06       0
#XS Ineff= 3 ,-1
       0     814    1855     814   820.9    1850     927    2500    1855
Permanent Ineff=
       F       F       F
#Block Obstruct= 9 ,-1
  159.68  187.38 1858.31  690.52  726.12 1858.31  732.34  813.31 1858.31
  928.83  941.29 1858.31  951.49   975.8 1858.31 1008.06 1077.97 1858.31
 1111.38 1168.24 1858.31 1285.92  1341.5 1858.31 1374.16 1383.08 1858.31
Bank Sta=846.02,920
XS Rating Curve= 0 ,0
Exp/Cntr=0.5,0.3

Type RM Length L Ch R = 1 ,465     ,58.5,58,58.4
XS GIS Cut Line= 4
     2170588.582      289102.371     2170349.888      289785.847
     2170649.886      290070.193     2171621.621      291014.537
#Sta/Elev= 30
       0 1898.76    64.1 1885.65    80.6 1877.99  140.981870.036  233.041863.518
   402.91858.857   585.3 1851.75   658.3 1851.84   706.5 1846.27  865.191847.443
   940.5 1847.79  945.65 1844.58   953.4 1839.43     970 1841.33   986.8 1839.43
  1001.1 1844.64  1023.4 1847.27 1076.82 1848.15  1158.2 1850.54 1276.941849.459
  1461.9 1850.39  1487.7 1849.77  1497.2 1847.65 1639.211852.716 1713.891851.241
 2294.551852.875  2316.3  1854.8  2397.5 1853.81  2475.3 1863.12  2492.3 1867.32
#Mann= 12 ,-1 , 0
       0     .12       0  140.98    .016       0  233.04     .06       0
   402.9    .016       0  865.19     .06       0  945.65     .04       0
  1001.1    .016       0 1076.82     .06       0 1276.94    .016       0
 1639.21     .06       0 1713.89    .016       0 2294.55     .06       0
#XS Ineff= 2 , 0
          927.14 1854.32    1006          1854.2
Permanent Ineff=
       F       F
#Block Obstruct= 16 ,-1
  149.49  221.09  1857.3  290.19  344.01  1857.3   494.6  541.61  1857.3
  658.55  684.43  1857.3  740.56  811.26  1857.3 1007.99 1027.61  1857.3
 1092.02 1166.13  1857.3 1196.17 1250.23  1857.3 1373.14 1470.03  1857.3
 1496.62 1530.49  1857.3 1557.18 1588.09  1857.3 1756.26 1791.35  1857.3
 1806.13 1845.46  1857.3 1874.39 1979.83  1857.3 2014.53 2038.23  1857.3
  2136.8 2174.65  1857.3
Bank Sta=945.65,1001.1
XS Rating Curve= 0 ,0
Exp/Cntr=0.3,0.1

Type RM Length L Ch R = 1 ,407     ,98.5,96.2,88.2
XS GIS Cut Line= 5
     2170568.713       289101.78     2170322.551      289827.608
     2170470.726      289977.076     2170576.422      290081.803
     2171583.931      291047.615
#Sta/Elev= 30
       0 1892.25    39.9  1885.2    59.1 1878.18    85.3 1876.02  122.091869.852
   248.1 1862.14  384.451858.807   570.2 1852.03   646.5 1851.66   678.8 1846.18
  725.571846.209   874.5 1847.09   906.8 1845.73   969.7 1847.71   992.9 1846.83
  996.65 1844.36  1000.3 1840.54  1004.5    1839  1034.7    1839 1046.11 1844.45
  1055.6 1846.57    1102 1847.25 1316.871848.037  1542.8 1848.22 1671.411850.442
 1749.461850.362 2325.911852.329    2406 1852.22  2465.8 1864.13  2521.4 1867.08
#Mann= 12 ,-1 , 0
       0     .12       0  122.09    .016       0   248.1     .06       0
  384.45    .016       0  725.57     .06       0  996.65     .04       0
 1046.11     .12       0    1102     .06       0 1316.87    .016       0
 1671.41     .06       0 1749.46    .016       0 2325.91     .06       0
#XS Ineff= 2 , 0
           972.5 1854.05  1086.5         1853.93
Permanent Ineff=
       F       F
#Block Obstruct= 10 ,-1
  127.03  233.05 1855.61  292.66   353.5 1855.61  501.63  533.91 1855.61
  645.23  700.86 1855.61  905.34  948.49 1855.61  1124.2 1203.78 1855.61
 1589.27 1620.45 1855.61 1931.18 2012.24 1855.61 2166.68 2280.94 1855.61
 2340.67 2396.97 1855.61
Bank Sta=996.65,1046.11
XS Rating Curve= 0 ,0
Exp/Cntr=0.3,0.1

Type RM Length L Ch R = 1 ,311     ,136.1,129.4,124.2
XS GIS Cut Line= 5
     2170545.564      289018.869     2170225.582      289893.451
     2170426.278      290064.142     2170510.522      290135.085
     2171480.065      291052.899
#Sta/Elev= 30
       0 1896.61    54.7  1882.9  141.711870.961  180.231867.469   209.2 1863.52
   286.1 1863.04  390.781858.495  407.851857.972   478.2  1857.1   569.4 1851.77
   645.9 1852.94  746.181845.942   943.3 1844.71  1076.8 1847.53  1192.2 1846.95
  1210.3 1846.73  1215.5 1843.62  1227.5 1838.25  1248.9 1838.25  1266.1 1843.85
  1280.7 1847.42 1304.931847.017    15111846.364 1859.611849.861 2027.011849.537
  2320.5  1848.9 2512.841852.099  2572.7 1853.63  2601.2 1862.04  2639.5 1864.72
#Mann= 14 ,-1 , 0
       0     .12       0  141.71     .06       0  180.23    .016       0
  390.78     .06       0  407.85    .016       0  746.18     .06       0
  1192.2    .016       0  1215.5     .04       0  1266.1     .12       0
 1304.93     .06       0    1511    .016       0 1859.61     .06       0
 2027.01    .016       0 2512.84     .06       0
#XS Ineff= 2 , 0
            1183 1852.85    1320         1852.73
Permanent Ineff=
       F       F
#Block Obstruct= 12 ,-1
  171.98  278.34 1855.04  496.66  513.28 1855.04  527.55  568.14 1855.04
  642.22  659.31 1855.04 1087.23 1149.28 1855.04 1358.38 1391.83 1855.04
 1604.28  1632.9 1855.04 1688.61 1719.54 1855.04 1982.62 1989.59 1855.04
  2251.8 2284.65 1855.04 2292.47 2338.14 1855.04 2392.46 2438.81 1855.04
Bank Sta=1215.5,1266.1
XS Rating Curve= 0 ,0
Exp/Cntr=0.3,0.1

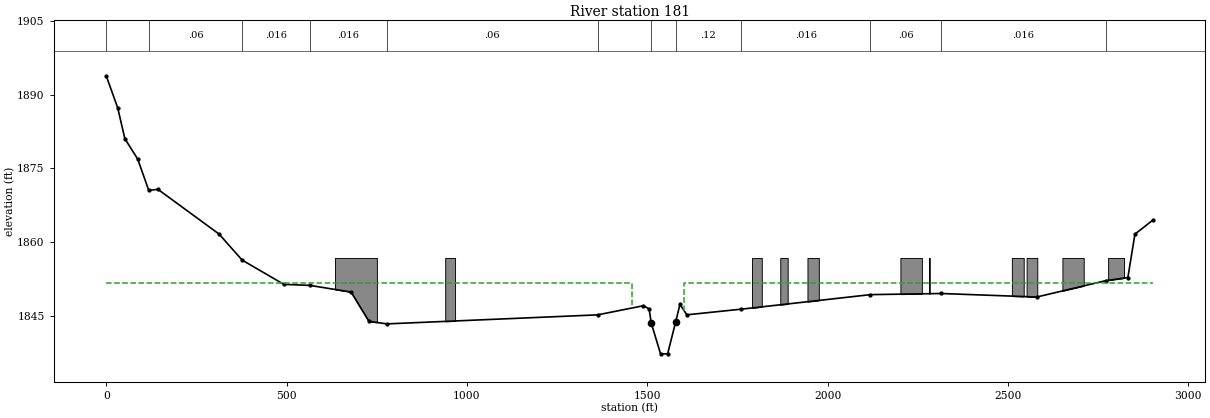
Type RM Length L Ch R = 1 ,181     ,181,181,181
XS GIS Cut Line= 6
     2170500.472      288933.594      2170059.13      289907.726
     2170375.226      290194.001     2170464.687      290239.726
      2170884.16      290520.037     2171466.651      291070.719
#Sta/Elev= 30
       0 1893.85    31.9 1887.33    51.7 1881.06    87.4 1876.89  117.981870.546
   143.6 1870.74   312.9 1861.65  377.051856.342   492.8 1851.41  564.521851.209
   678.9 1849.85   728.4 1843.89  778.521843.375  1362.5 1845.21  1489.6 1847.07
  1505.4 1846.42 1510.951843.598    1537 1837.28  1556.6 1837.28  1578.5 1843.67
  1590.7 1847.34  1609.8 1845.22 1760.411846.365 2119.021849.325 2314.521849.556
    2580 1848.84 2771.871852.176  2832.6  1852.8  2852.2 1861.63  2902.5 1864.52
#Mann= 12 ,-1 , 0
       0     .12       0  117.98     .06       0  377.05    .016       0
  564.52    .016       0  778.52     .06       0  1362.5    .016       0
 1510.95     .04       0  1578.5     .12       0 1760.41    .016       0
 2119.02     .06       0 2314.52    .016       0 2771.87     .06       0
#XS Ineff= 2 , 0
         1457.25 1851.62 1602.23         1851.62
Permanent Ineff=
       F       F
#Block Obstruct= 15 ,-1
  194.29  214.05 1856.79  230.24  251.12 1856.79   330.1   362.1 1856.79
  634.39  750.48 1856.79  939.88  967.25 1856.79 1790.63 1817.64 1856.79
 1868.91 1889.43 1856.79 1944.27 1975.79 1856.79 2201.99 2261.47 1856.79
 2281.68 2283.13 1856.79 2511.02 2543.86 1856.79 2551.86 2581.49 1856.79
 2651.18 2710.23 1856.79 2777.86 2821.83 1856.79  2860.7  2902.5 1856.79
Bank Sta=1510.95,1578.5
XS Rating Curve= 0 ,0
Exp/Cntr=0.3,0.1
LCMann Table=0

Chan Stop Cuts=-1
Use User Specified Reach Order=0
Composite Channel Slope=5